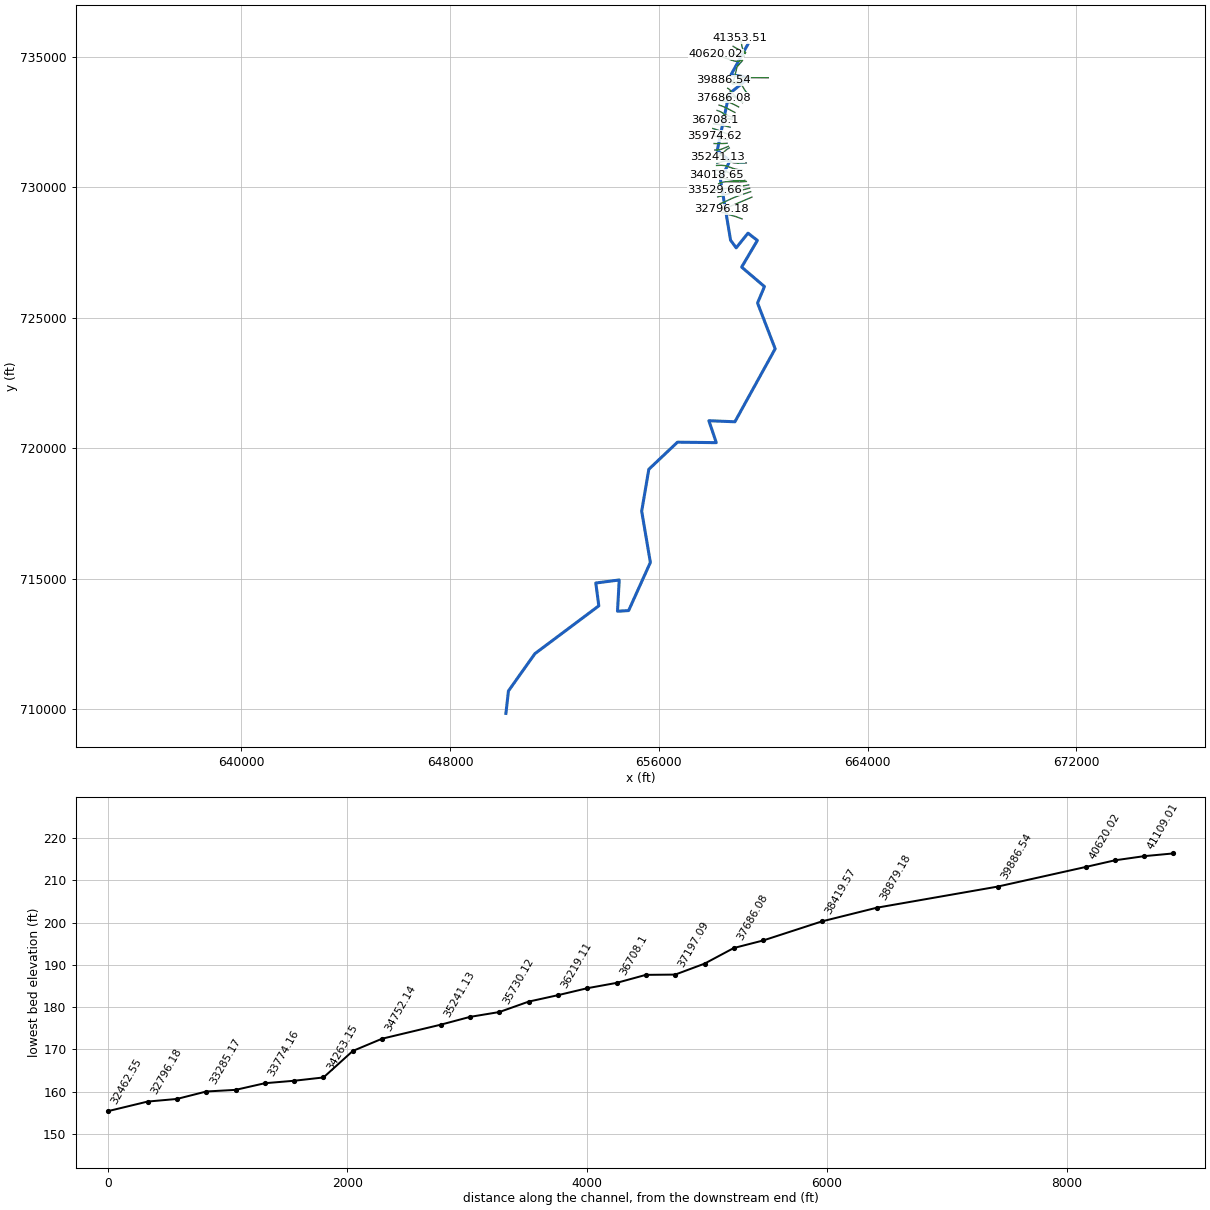
--- 4379_ras.prj (project) ---

Proj Title=4379
Current Plan=p01
Default Exp/Contr=0.3,0.1
English Units
Geom File=g01
Flow File=f01
Plan File=p01
Y Axis Title=Elevation
X Axis Title(PF)=Main Channel Distance
X Axis Title(XS)=Station
BEGIN DESCRIPTION:
RFD model 4379 exported to HEC-RAS
END DESCRIPTION:

--- 4379_ras.p01 (plan) ---

Plan Title=Plan 01
Program Version=4.10
Short Identifier=Plan 01
Geom File=g01
Flow File=f01
Subcritical Flow
Calc Critical at every XS
Secant Critical Depth

--- 4379_ras.f01 (steady flow) ---

Flow Title=Flow 01
Program Version=5.01
Number of Profiles= 6
Profile Names=10yr,25yr,50yr,100yr,100plus,500yr
River Rch & RM=4379,71,41353.51
 5694.9510134.3414710.4419338.8428234.7132960.64
River Rch & RM=4379,71,41109.01
  5696.610138.0114716.47 19347.6 28247.532976.64
River Rch & RM=4379,71,40864.52
 5697.6410140.3414720.3119353.1928255.6632986.88
River Rch & RM=4379,71,40620.02
 5698.56 10142.414723.68 19358.128262.8332995.85
River Rch & RM=4379,71,39886.54
 5707.6210162.2914756.1619405.0928331.4333080.93
River Rch & RM=4379,71,38879.18
 5712.2710172.8414773.6419430.6728368.7833128.23
River Rch & RM=4379,71,38419.57
 5713.5410175.7714778.5319437.8628379.2833141.65
River Rch & RM=4379,71,37930.58
 5715.4610180.14 14785.819448.5328394.8533161.46
River Rch & RM=4379,71,37686.08
  5717.4 10184.514792.9819458.9828410.1233180.62
River Rch & RM=4379,71,37441.59
 5718.1710186.2314795.8419463.15 28416.233188.29
River Rch & RM=4379,71,37197.09
 5766.7910287.3414956.5919691.1328749.0533584.56
River Rch & RM=4379,71, 36952.6
 5767.3710288.6414958.7419694.2628753.6233590.29
River Rch & RM=4379,71, 36708.1
 5768.4110290.9614962.5519699.8128761.7333600.45
River Rch & RM=4379,71,36463.61
  5771.510298.0114974.2619716.9728786.7833632.22
River Rch & RM=4379,71,36219.11
 5772.6410300.57 14978.519723.1828795.8433643.66
River Rch & RM=4379,71,35974.62
 5775.1910306.3714988.1219737.26 28816.433669.69
River Rch & RM=4379,71,35730.12
 5776.3210308.9314992.3619743.4628825.4533681.13
River Rch & RM=4379,71,35485.63
 5778.0910312.9214998.9619753.1128839.54 33698.9
River Rch & RM=4379,71,35241.13
  5778.910314.7715002.0219757.5828846.0733707.15
River Rch & RM=4379,71,34752.14
  5804.810374.41 15101.619904.11   2906033980.28
River Rch & RM=4379,71,34507.64
 5805.5510376.1115104.4219908.2229066.0133987.87
River Rch & RM=4379,71,34263.15
 5806.9110379.2115109.5619915.75   2907734001.79
River Rch & RM=4379,71,34018.65
 5807.5410380.62 15111.919919.1829082.0134008.11
River Rch & RM=4379,71,33774.16
 5807.9110381.4715113.3119921.2429085.0134011.91
River Rch & RM=4379,71,33529.66
  5903.810579.3515426.8420364.8329732.6534776.38
River Rch & RM=4379,71,33285.17
 5904.3710580.6215428.94 20367.929737.1334782.02
River Rch & RM=4379,71,33040.67
 5905.5810583.3915433.5520374.6729747.0234794.55
River Rch & RM=4379,71,32796.18
 5907.3910587.5315440.4520384.8129761.8234813.36
River Rch & RM=4379,71,32462.55
 5909.2110591.6915447.3620394.9629776.6434832.16
River Rch & RM=4379,71,31901.11
    591110595.7515454.0920404.8229791.0434850.33
River Rch & RM=4379,71,31586.75
 6116.5411024.5116137.67   2137731210.4236535.93
River Rch & RM=4379,71,29170.22
 6304.4911445.02 16832.322392.6632693.2838385.91
River Rch & RM=4379,71,28779.71
 6310.5111458.4716854.5222425.1632740.73   38445
River Rch & RM=4379,71,27673.73
 6321.1311482.3616894.1122483.22 32825.538551.03
River Rch & RM=4379,71,27026.15
 6423.8211720.79 17295.223077.9833693.8639658.72
River Rch & RM=4379,71,26529.07
  6441.611759.9917359.6123171.8833830.9539827.68
River Rch & RM=4379,71,26280.53
 6442.1211761.1717361.5823174.7933835.1939833.04
River Rch & RM=4379,71,26118.65
 6443.31 11763.917366.1623181.5533845.0639845.52
River Rch & RM=4379,71,26006.12
 6444.1111765.7317369.2123186.0633851.6439853.84
River Rch & RM=4379,71,25783.46
 6445.97   1177017376.3723196.6533867.1239873.45
River Rch & RM=4379,71,25534.92
 6451.8411783.3917398.71 23229.633915.2139934.04
River Rch & RM=4379,71,25286.39
 6452.8911785.82 17402.823235.6633924.0739945.32
River Rch & RM=4379,71,25037.85
 6455.0811790.9117411.38 23248.433942.6639969.07
River Rch & RM=4379,71,24789.31
 6455.8411792.6917414.3823252.8633949.1739977.38
River Rch & RM=4379,71,24540.77
 6456.91 11795.217418.6323259.1933958.4139989.25
River Rch & RM=4379,71,24292.24
 6458.2311798.2617423.7823266.8433969.5840003.49
River Rch & RM=4379,71, 24043.7
 6495.1911886.0917573.1823490.2934295.8240425.14
River Rch & RM=4379,71,23795.16
 6496.2711888.6617577.5623496.8534305.4140437.55
River Rch & RM=4379,71,23546.62
 6497.5611891.7217582.7923504.6734316.8240452.32
River Rch & RM=4379,71,23049.55
 6502.3311903.0517602.0523533.4834358.8840506.66
River Rch & RM=4379,71,22801.01
 6502.89 11904.417604.3423536.9234363.9140513.16
River Rch & RM=4379,71,22552.47
 6504.0311907.0917608.94 23543.834373.9540526.15
River Rch & RM=4379,71,22303.94
 6504.7311908.7817611.8223548.1434380.2940534.41
River Rch & RM=4379,71, 22055.4
 6509.7911920.9117632.5623579.2534425.7140593.43
River Rch & RM=4379,71,21558.33
 6530.32 11968.4 17712.423697.6834598.6240813.28
River Rch & RM=4379,71,20812.71
 6540.5911993.8317756.4523764.4634696.1140942.14
River Rch & RM=4379,71,19818.56
 6562.6812048.7317851.7423909.0534907.2141221.68
River Rch & RM=4379,71,18824.42
 6564.7812054.0917861.1423923.42 34928.241249.83
River Rch & RM=4379,71,17084.65
 6621.6712192.9318100.3424284.7135455.6841941.76
River Rch & RM=4379,71,16467.03
 6626.6212205.7118122.8824319.31 35506.242009.89
River Rch & RM=4379,71,15298.02
 6631.1212217.5618143.9424351.8135553.6542074.48
River Rch & RM=4379,71,14129.02
 6633.9912225.2918157.7824373.29   3558542117.53
River Rch & RM=4379,71,12629.05
 6683.2912356.6818392.5224736.9436115.9442844.33
River Rch & RM=4379,71,10751.37
 6694.4512387.4318448.1324823.83 36242.843020.38
River Rch & RM=4379,71,6382.856
  6738.7 12507.818665.0525162.0536736.5943702.82
River Rch & RM=4379,71,5029.352
 6750.5612540.3118723.8525253.9536870.7743888.95
River Rch & RM=4379,71, 4901.74
 6751.3612542.5118727.8225260.1636879.8443901.54
River Rch & RM=4379,71,3957.182
 6757.2812558.7218757.1125305.9336946.6643994.18
River Rch & RM=4379,71,2183.281
 6797.3412668.0818954.6925614.72 37397.5   44619
River Rch & RM=4379,71, 62.3688
 6808.3412698.2419009.2825700.1837522.2644792.27
Boundary for River Rch & Prof#=4379,71,1
Up Type= 0
Dn Type= 2
Boundary for River Rch & Prof#=4379,71,2
Up Type= 0
Dn Type= 2
Boundary for River Rch & Prof#=4379,71,2
Up Type= 0
Dn Type= 2
Boundary for River Rch & Prof#=4379,71,2
Up Type= 0
Dn Type= 2
Boundary for River Rch & Prof#=4379,71,2
Up Type= 0
Dn Type= 2
Boundary for River Rch & Prof#=4379,71,2
Up Type= 0
Dn Type= 2

--- 4379_ras.g01 (geometry) ---

Geom Title=4379
Program Version=4.10

River Reach=4379,71
Reach XY= 30
659410.676493406735484.798641974658765.890228659 734320.72203236
659468.425142706734210.703558093658689.863139689733586.591787701
658238.469450146731424.858337558658721.449717402731018.109375899
658360.564972549730297.551192861658749.287483959727980.441729227
658963.100589036727686.701119957659416.203436194728249.027273772
659776.016075464 727970.34102114659172.739823609 726948.32876541
 660047.35982147726203.136772165659782.522880612725571.943940438
660457.792322516723818.114989121658914.467325062721020.728662676
657917.250737043721061.540191937658201.413597169 720221.07285511
656714.785236925720238.938581726655615.709191708719199.951584744
655342.484750359717594.732427127655674.966558097715631.473669147
654842.619411437713786.071660303654415.335380614713760.311995991
654482.175658556714958.228662662653584.900120737714841.527958985
653698.715050848  713966.6447636651251.327330529712135.270880123
650236.515936165710706.492551559650139.293713955709846.249496004

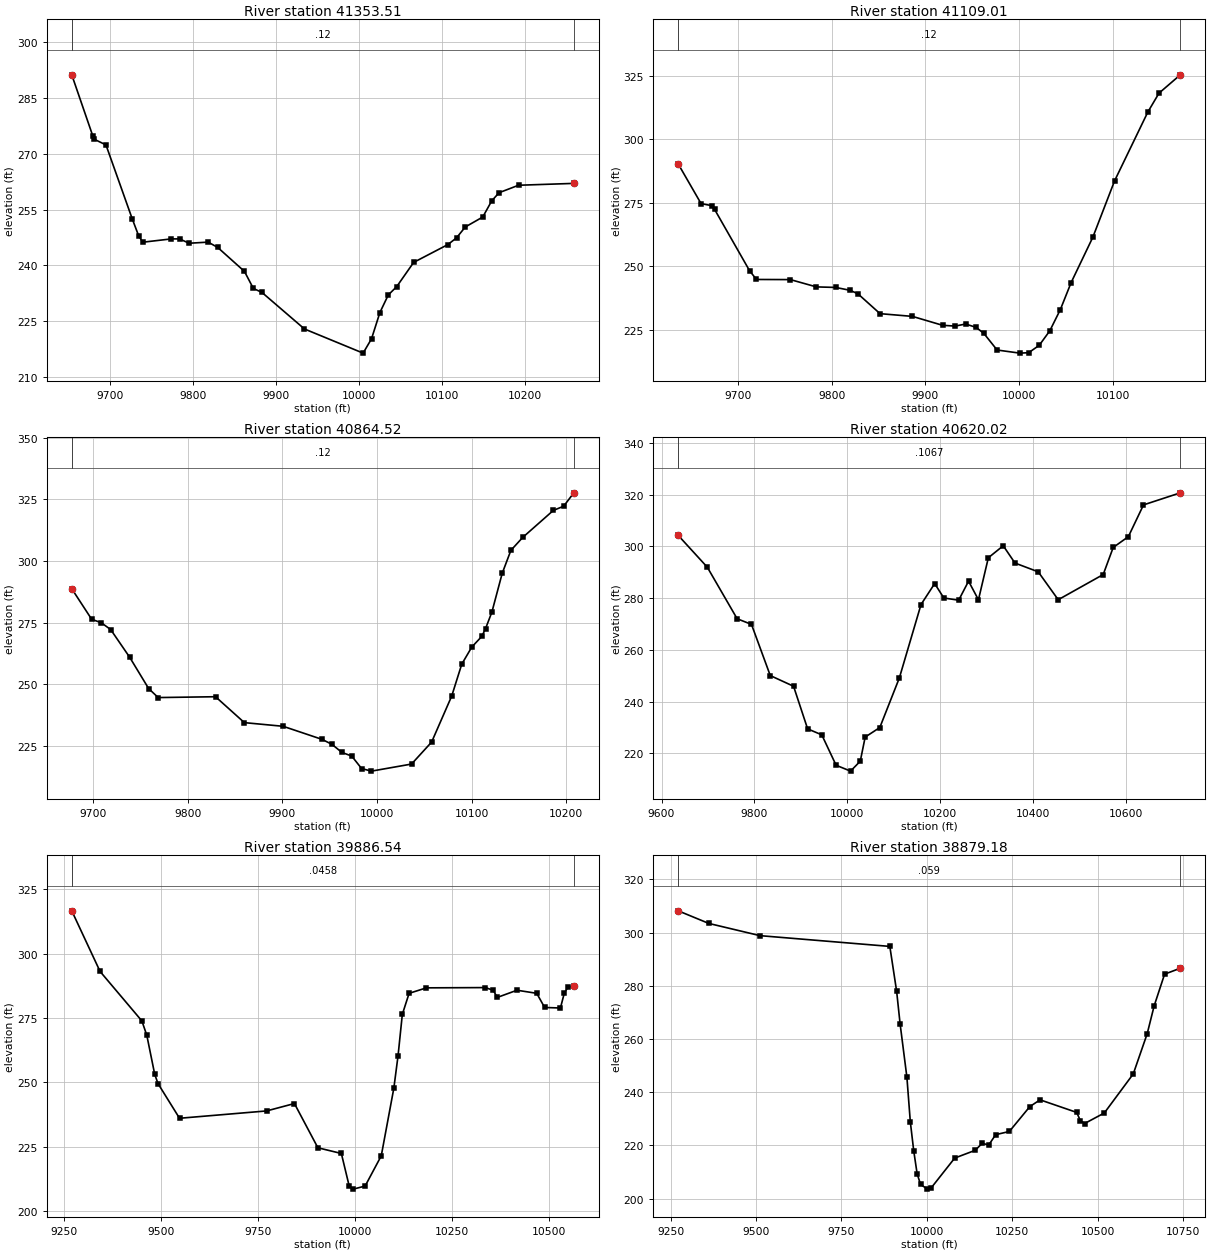
Type RM Length L Ch R = 1 ,41353.51,244.495200,244.495200,244.495200
XS GIS Cut Line= 6
659325.151452428735168.204111497659272.788532624735218.735569581
659216.548826096 735305.08074893659190.291749877735383.026800912
659153.588073794735581.790927548659097.115481759735715.059445843
#Sta/Elev= 30
9653.657291.28299679.032274.83249680.706273.95659694.921 272.4259726.497252.6034
9734.373 247.9679739.347246.24859773.793247.14239783.727247.13599795.217245.9719
9818.197246.27139829.687244.85359861.993238.39849872.726 233.8149883.096232.7424
 9934.38222.908410005.17 216.407 10015.3220.252610025.43227.333910035.55232.0638
 10045.7234.297810066.15  240.8210107.44245.612910117.88 247.42110128.43250.3433
10149.54253.031210160.33257.365710169.18259.566110192.69261.574310259.43262.0743
#Mann= 3 , 0 , 0
9653.657    0.12       09653.657    0.12       010259.43    0.12       0
#XS Ineff= 2 , 0
       0                               0
Bank Sta=9653.657,10259.43
Exp/Cntr=0.3,0.1

Type RM Length L Ch R = 1 ,41109.01,244.495200,244.495200,244.495200
XS GIS Cut Line= 6
659305.822881749735134.818398506659252.053785277735167.554103226
659118.741799936735255.982281486659065.576363401 735285.73897312
658951.723148813735344.228278644658846.099055844735409.867761498
#Sta/Elev= 30
9636.159290.24589660.538274.65619672.245273.82979674.968272.38939712.386248.1964
9719.708244.76789755.944244.71739783.706241.84349804.258241.63339819.713240.5037
9828.075239.12329851.707231.2995 9886.31230.22589918.515226.71619931.887226.4054
  9943.1227.21649954.313225.90649962.608223.51539976.739216.9782   10001215.7555
10010.42215.917610021.73218.827110033.03224.545710044.33232.937110055.83243.5646
10079.01261.4209 10102.2283.599810137.79310.753810149.67 318.16110172.43325.3771
#Mann= 3 , 0 , 0
9636.159    0.12       09636.159    0.12       010172.43    0.12       0
#XS Ineff= 2 , 0
       0                               0
Bank Sta=9636.159,10172.43
Exp/Cntr=0.3,0.1

Type RM Length L Ch R = 1 ,40864.52,244.495200,244.495200,244.495200
XS GIS Cut Line= 6
 659246.00979554735031.504885966659111.329193829735043.672923504
658992.916737908735068.017159712658927.778929122735087.299448011
658816.901484708 735126.57410276658735.002763258735160.362430122
#Sta/Elev= 30
9677.526288.6946 9698.58276.30359708.601274.93749718.623272.15869738.665260.9465
9758.746248.22899768.818244.58659829.386244.92629859.848234.42579900.791232.9393
9941.994227.6307 9952.42225.60789962.845222.35659973.271220.87059983.697215.8052
9994.123214.767110036.45217.634210057.66226.543910078.88245.201710089.49258.1232
 10100.1265.063210110.71269.409710114.59272.498710121.36  279.2810132.18   294.9
10141.39304.256210153.81309.474210186.26320.459110197.08322.1359 10207.9327.5793
#Mann= 3 , 0 , 0
9677.526    0.12       09677.526    0.12       0 10207.9    0.12       0
#XS Ineff= 2 , 0
       0                               0
Bank Sta=9677.526,10207.9
Exp/Cntr=0.3,0.1

Type RM Length L Ch R = 1 ,40620.02,733.485600,733.485600,733.485600
XS GIS Cut Line= 6
659201.653271198734893.629966592659096.038282003 734847.65193005
659036.149858054734833.437506175658891.668847801734844.420145846
658549.568229079734959.934419297658182.071566438735109.248007295
#Sta/Elev= 30
9636.009304.22649698.584291.94459762.785 272.0389793.644269.86519834.051250.0938
9884.166245.97059914.409229.51799944.921227.1954 9975.72215.455310006.82213.1845
10027.76217.039310038.26226.334710069.77230.026510111.86 249.19810158.45 277.543
10187.81285.622210207.58280.056710239.49279.209210260.76286.553810282.03279.3678
10303.31 295.60310335.39300.237110360.64293.557710410.68290.1646 10453.7279.3923
 10550.5289.122510572.02299.584410604.61303.7466 10637.2316.017210716.42 320.681
#Mann= 3 , 0 , 0
9636.009  0.1067       09636.009  0.1067       010716.42  0.1067       0
#XS Ineff= 2 , 0
       0                10178.07       0
Bank Sta=9636.009,10716.42
Exp/Cntr=0.3,0.1

Type RM Length L Ch R = 1 ,39886.54,1007.353600,1007.353600,1007.353600
XS GIS Cut Line= 6
659201.653271198734857.865626642658996.122928865734619.892429693
658884.413575271734152.813380582658834.087406012734061.234922845
658807.535883456734036.387412393658461.023792386734102.113803819
#Sta/Elev= 30
9269.432316.70179342.396293.13369450.133273.90819462.779  268.349483.252253.1131
9491.787249.52599547.161236.07959771.594238.93219843.232241.80719903.717224.6106
9964.173222.3971 9984.45209.69489994.592208.5415 10025.4209.727210067.03221.4863
10099.43247.7735 10110.3260.394210121.29276.451710138.73284.6364 10183.4286.7675
10335.36286.869710355.72285.8103 10365.9283.037310416.79 285.84210467.68284.6455
10488.04279.136410528.75278.938510538.93 284.82410549.11 287.23910563.33287.2971
#Mann= 3 , 0 , 0
9269.432  0.0458       09269.432  0.0458       010563.33  0.0458       0
#XS Ineff= 2 , 0
       09802.729                       0
Bank Sta=9269.432,10563.33
Exp/Cntr=0.3,0.1

Type RM Length L Ch R = 1 ,38879.18,459.617500,459.617500,459.617500
XS GIS Cut Line= 6
660194.610774249734202.577739432659610.518125385734207.250480637
659154.925859243734202.577739432659108.198447376  734113.7956568
658991.379917562734046.040909544658799.797528774734008.658980027
#Sta/Elev= 30
9272.154308.21629361.768 303.4719511.773298.87679891.786294.83449911.787277.8868
9921.787265.80889941.788245.60439951.789228.86259961.789217.9416 9971.79209.2892
 9981.79205.312210001.79203.543510011.79203.8268 10081.8215.2242 10141.8218.1436
 10161.8220.7254 10181.8220.2208 10201.8224.0289 10241.8 225.22810301.81234.5892
10331.75237.131310439.03 232.39410449.67229.311710462.15228.214810519.95232.1862
 10604.7246.878410645.45261.993510665.83272.4531 10696.4284.394510742.45286.6267
#Mann= 3 , 0 , 0
9272.154   0.059       09272.154   0.059       010742.45   0.059       0
#XS Ineff= 2 , 0
       0                               0
Bank Sta=9272.154,10742.45
Exp/Cntr=0.3,0.1

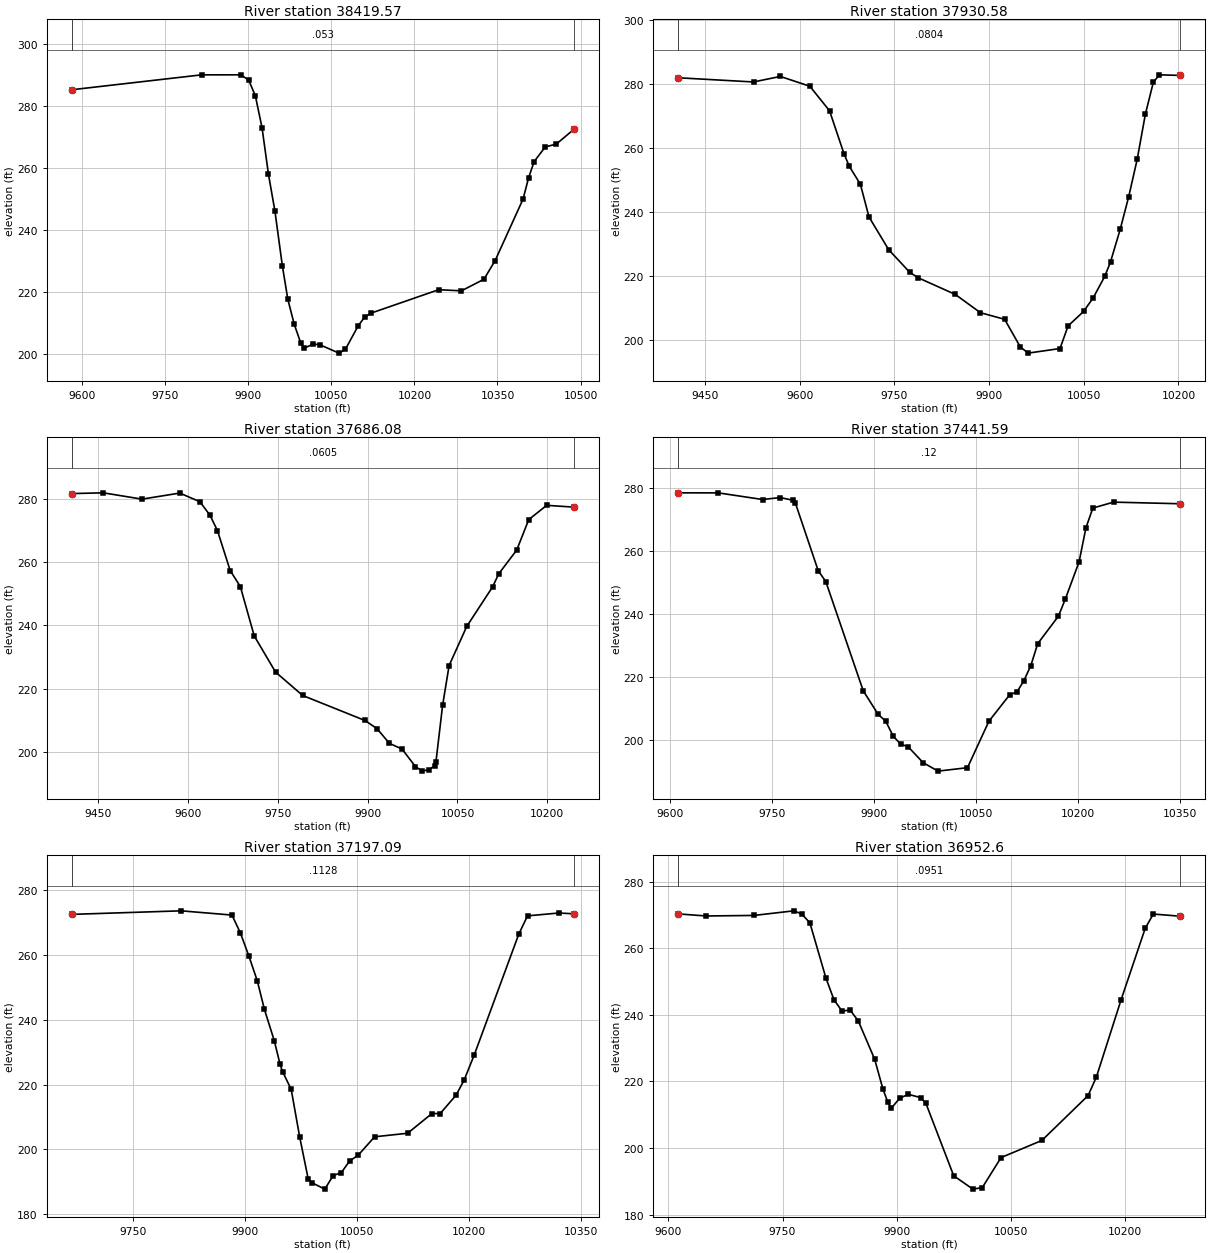
Type RM Length L Ch R = 1 ,38419.57,488.990400,488.990400,488.990400
XS GIS Cut Line= 6
659484.015601124733512.932568296659314.187257849733699.161439493
659167.367771194733940.748655182659120.194957842733992.432384543
659102.417156969733997.975125848658823.350136188 733962.59768494
#Sta/Elev= 30
9581.321285.34259815.925290.15469886.501290.16019900.845288.45699912.854283.3515
9924.863273.10669936.536258.00079948.159246.14759961.531228.54429971.406 217.718
 9983.03209.59389994.653203.632410000.76201.889410017.76203.228610029.29202.9951
10063.87200.2914 10075.4201.522410098.45209.087310109.98211.891210121.89213.2177
 10243.8220.769910284.91220.408710325.62224.144310345.84230.195710396.18250.0221
 10406.2256.906110416.21 262.14310436.23266.860810456.25267.798910487.92272.5452
#Mann= 3 , 0 , 0
9581.321   0.053       09581.321   0.053       010487.92   0.053       0
#XS Ineff= 2 , 0
       0                               0
Bank Sta=9581.321,10487.92
Exp/Cntr=0.3,0.1

Type RM Length L Ch R = 1 ,37930.58,244.495200,244.495200,244.495200
XS GIS Cut Line= 6
659217.519419498733262.550109263 658893.48279147733533.136432382
658850.014895493733580.276632865658732.511835423733728.757882754
 658679.59563802733776.313413535658639.124171488733802.644831931
#Sta/Elev= 30
9407.542281.83689526.809 280.5269569.236282.25849616.057279.18879647.272271.5098
9670.083258.12859678.486254.17219696.133248.5401  9709.7238.34959740.914228.1106
9774.282221.04389787.629219.32939846.477214.11979886.268208.41369924.562206.3479
9949.371197.74929961.775195.7778 10012.3197.215210025.24 204.30610049.67208.7963
10064.92213.062710083.39219.828210092.33224.286110107.85234.579310121.21244.7122
10134.58256.327210147.57270.457210160.19280.439610169.78282.758910202.92282.5789
#Mann= 3 , 0 , 0
9407.542  0.0804       09407.542  0.0804       010202.92  0.0804       0
#XS Ineff= 2 , 0
       0                               0
Bank Sta=9407.542,10202.92
Exp/Cntr=0.3,0.1

Type RM Length L Ch R = 1 ,37686.08,244.495200,244.495200,244.495200
XS GIS Cut Line= 6
659206.669309075733252.356052028658978.682879735733429.064740319
658844.730854376733497.585229593658763.478968356733500.199607061
658618.793784217733439.658929091658459.706406436733433.888788396
#Sta/Elev= 30
9405.612281.62099458.298281.86169522.857279.86999586.099281.78099619.695279.0441
9636.541274.79339649.039269.91149670.332257.29099687.228252.28399710.469236.6677
9746.026225.27879791.397217.87969895.499209.98249915.632207.39619936.261202.7651
9957.442200.96359979.797195.43099991.191193.9971 10002.6194.483510011.84195.6752
10014.01196.867610025.16214.741110036.06227.345210065.48239.672210108.83252.2158
10118.96256.303110149.03263.797710169.06273.406610199.07277.908810244.44277.3521
#Mann= 3 , 0 , 0
9405.612  0.0605       09405.612  0.0605       010244.44  0.0605       0
#XS Ineff= 2 , 0
       0                               0
Bank Sta=9405.612,10244.44
Exp/Cntr=0.3,0.1

Type RM Length L Ch R = 1 ,37441.59,244.495200,244.495200,244.495200
XS GIS Cut Line= 6
659056.682059909733085.177797949658951.684941047733143.298133164
658862.511299063733187.610095088658674.669206315733271.384508234
658575.447026828733296.239765682658368.025150823733328.308199757
#Sta/Elev= 30
9612.544278.44999671.618278.42739736.378276.33499762.352276.94569781.322276.0853
9784.685275.18289818.185253.78089829.352250.3249 9884.33215.72819906.304208.2501
9917.291206.13099928.277201.39039939.264198.83919950.251198.01879972.224192.9841
9994.198190.287210037.48191.377210068.99206.109110099.78214.550410110.01215.3241
10120.23218.901410130.46223.688810140.69230.687610171.04239.363310181.16244.7707
 10201.4256.586210211.52267.408210221.64273.622210251.99275.501410350.12274.9875
#Mann= 3 , 0 , 0
9612.544    0.12       09612.544    0.12       010350.12    0.12       0
#XS Ineff= 2 , 0
       0                               0
Bank Sta=9612.544,10350.12
Exp/Cntr=0.3,0.1

Type RM Length L Ch R = 1 ,37197.09,244.495200,244.495200,244.495200
XS GIS Cut Line= 6
658915.517302217732875.338293233658820.694870817732923.126330929
658630.828878561733024.995772642658525.910503719733076.298839151
658402.488876167733126.299645753658305.639286014733156.918461274
#Sta/Elev= 30
9667.654272.61439814.346273.71219882.436272.40259893.784266.86499905.133 259.733
9916.481252.0295 9925.86243.33929939.178233.58229947.012226.21859950.527223.9055
9961.875218.53139973.223203.86149984.572190.97759989.315189.713510006.95   187.7
10018.08191.879510029.21192.825310040.34196.435510051.47198.120110073.72203.8757
10117.99204.970110150.69211.073610161.59211.035910183.11216.784510193.81221.4351
10207.53229.300210267.17266.582810278.76272.155910320.72273.037310340.88272.7956
#Mann= 3 , 0 , 0
9667.654  0.1128       09667.654  0.1128       010340.88  0.1128       0
#XS Ineff= 2 , 0
       0                               0
Bank Sta=9667.654,10340.88
Exp/Cntr=0.3,0.1

Type RM Length L Ch R = 1 , 36952.6,244.495200,244.495200,244.495200
XS GIS Cut Line= 6
658829.869418065 732687.30557025658563.869206877732777.143399949
658505.085756594732811.669653567658398.199612827732885.899109477
658309.135598394732926.399543232658231.193725407732952.397690378
#Sta/Elev= 30
9613.002270.36069649.561269.73219712.467269.89469764.888271.28089775.383270.3078
9785.937267.66539807.046251.04919817.601244.53139828.155241.1529 9838.71241.4581
9849.372238.24749871.029226.67729881.858217.72929888.324213.76379892.686211.8983
9903.923214.95669915.212216.12769931.618215.13149938.394213.38289974.855191.6528
10000.03187.636210012.38188.093210037.04197.115710090.68202.270110151.42215.7596
10162.27221.324910194.72 244.537 10226.5266.070910237.09270.312210272.52269.6573
#Mann= 3 , 0 , 0
9613.002  0.0951       09613.002  0.0951       010272.52  0.0951       0
#XS Ineff= 2 , 0
       0                               0
Bank Sta=9613.002,10272.52
Exp/Cntr=0.3,0.1

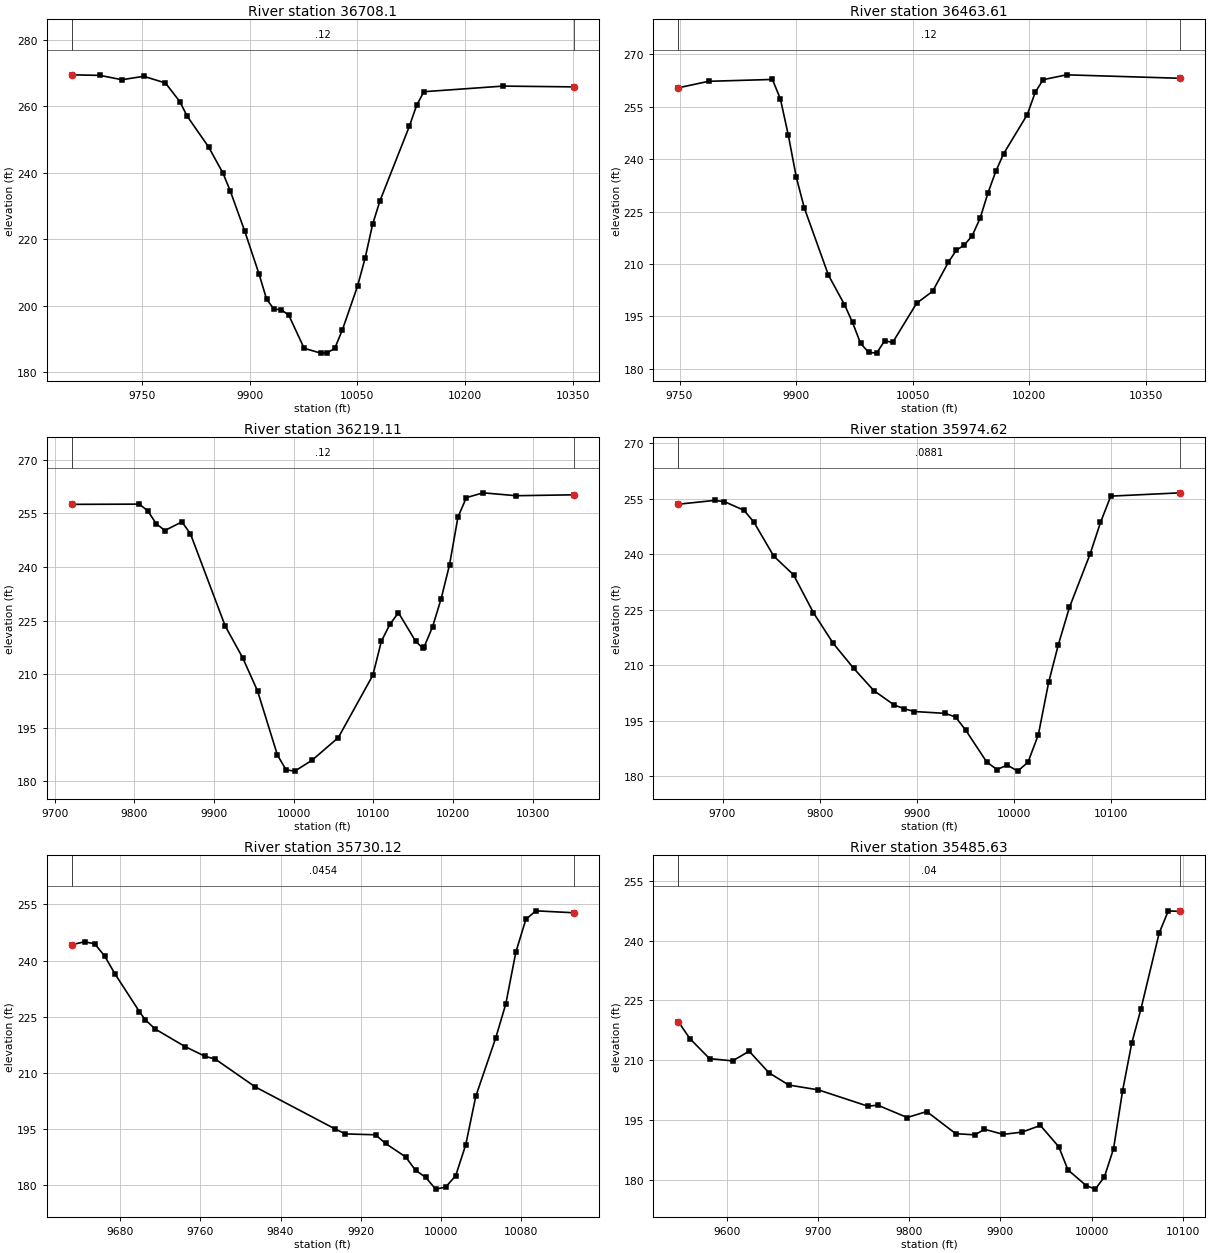
Type RM Length L Ch R = 1 , 36708.1,244.495100,244.495100,244.495100
XS GIS Cut Line= 6
658813.450431408732616.156628069658608.684775026732640.908646975
658519.379485236732625.432608416658361.701873755732575.403138231
658260.837294787732566.041245381658126.552005265732571.640282796
#Sta/Elev= 30
9652.265269.44589691.515269.2783 9722.14267.97089752.481 269.0049782.718266.9915
9802.784261.38149812.817257.06269842.817247.74729862.833239.87649872.878234.5967
9892.967222.53199913.277209.39789923.496202.02249933.833198.9423 9944.17198.8098
9954.637 197.0729975.904187.1906    9999185.733710007.88185.802310018.58187.1772
10029.29192.815710050.35205.954110060.82214.325310071.29  224.5210081.56231.5818
10122.43253.969310132.52260.253310142.61264.368210252.88266.055810351.51265.8195
#Mann= 3 , 0 , 0
9652.265    0.12       09652.265    0.12       010351.51    0.12       0
#XS Ineff= 2 , 0
       0                               0
Bank Sta=9652.265,10351.51
Exp/Cntr=0.3,0.1

Type RM Length L Ch R = 1 ,36463.61,244.495200,244.495200,244.495200
XS GIS Cut Line= 6
658733.128507119732310.109638763658669.873003644732324.102162371
658565.760252703732348.979010571658440.174170563732382.026827768
658363.677145831732397.969533814 658100.34486054 732438.66328917
#Sta/Elev= 30
9748.345260.40159787.395262.26899869.547262.80019879.829257.2423 9890.11246.7751
9900.392234.74399910.673225.99479941.648206.81829962.337198.34769972.681193.2766
9983.026187.2699 9993.37184.730110003.71184.473210014.04188.004810024.38187.5346
10055.32198.783610075.75 202.15110096.18210.524910106.39213.941510116.61215.4039
10126.82218.118510136.96223.094410147.07230.331110157.19236.546810167.31241.6005
10197.67252.742610207.79259.072710217.91262.729110248.26264.123810394.63263.1332
#Mann= 3 , 0 , 0
9748.345    0.12       09748.345    0.12       010394.63    0.12       0
#XS Ineff= 2 , 0
       0                               0
Bank Sta=9748.345,10394.63
Exp/Cntr=0.3,0.1

Type RM Length L Ch R = 1 ,36219.11,244.495200,244.495200,244.495200
XS GIS Cut Line= 6
658655.651241367732042.222143657658568.673090771732070.619172087
658513.603370135732091.864071861658323.019867758732175.560040344
 658224.38957754732213.469383001658065.098595667732259.821130334
#Sta/Elev= 30
9721.282257.5454 9806.11257.61039816.732 255.711 9827.45252.08819838.168250.2214
9859.605252.64639870.323249.26169913.959223.4423 9935.79214.59899954.468205.3059
9979.453187.33459990.369183.1634 10001.3 182.82410023.16185.914710055.95 192.234
10099.28209.698110109.99219.2147 10120.7223.968710131.42227.181710152.84219.2538
10162.03217.251610163.56217.567110174.27223.261710184.98231.101110195.51240.5884
10206.03253.888710216.55259.422610237.58260.775410279.24259.9664 10351.6260.2192
#Mann= 3 , 0 , 0
9721.282    0.12       09721.282    0.12       0 10351.6    0.12       0
#XS Ineff= 2 , 0
       0                               0
Bank Sta=9721.282,10351.6
Exp/Cntr=0.3,0.1

Type RM Length L Ch R = 1 ,35974.62,244.495200,244.495200,244.495200
XS GIS Cut Line= 6
 658631.97191351731831.929952035658560.663097144731842.004432179
658476.213987562731860.289015462 658389.27659287731885.928302184
658210.221331725731951.873600814658136.725119184731975.124277398
#Sta/Elev= 30
9654.389253.54379691.728254.57349701.827 254.2549722.026251.9082  9732.2248.7305
9752.663239.51559773.127 234.428 9793.59224.18079814.077 215.8489834.929209.1579
 9855.78203.09339876.632199.22589887.058198.17959897.484197.43329929.303196.9319
9939.952  195.95  9950.6192.30599971.898183.80799982.547181.72379993.196182.9488
10003.86181.298110014.53183.709510025.19191.170510035.85205.421610045.66215.4232
10057.18225.615810078.51240.098410089.17248.604310099.74255.735410171.35256.6287
#Mann= 3 , 0 , 0
9654.389  0.0881       09654.389  0.0881       010171.35  0.0881       0
#XS Ineff= 2 , 0
       0                               0
Bank Sta=9654.389,10171.35
Exp/Cntr=0.3,0.1

Type RM Length L Ch R = 1 ,35730.12,244.495200,244.495200,244.495200
XS GIS Cut Line= 6
658617.860850585731694.085493379658550.639153866 731688.05031619
658455.658334455731684.262788664 658316.08901283731684.107092493
658223.746573206731680.356528884658117.175742118731683.915871304
#Sta/Elev= 30
9631.623244.24799644.536 245.0139654.576244.46329664.616241.13569674.657236.4626
9699.115226.33749704.759224.20869714.767221.69579744.791216.96239764.807214.3567
9774.815213.6363 9814.83206.1778 9894.83194.8824 9904.83 193.6079934.831193.3698
9944.838191.05279964.852187.46679974.859183.85859984.866181.99599994.873178.8299
10004.89179.3708 10014.9182.442910024.91 190.69310034.91203.645710054.91 219.341
10064.91228.394310074.91 242.23410084.92251.005710094.94 253.30110132.83252.7815
#Mann= 3 , 0 , 0
9631.623  0.0454       09631.623  0.0454       010132.83  0.0454       0
#XS Ineff= 2 , 0
       0                               0
Bank Sta=9631.623,10132.83
Exp/Cntr=0.3,0.1

Type RM Length L Ch R = 1 ,35485.63,244.495200,244.495200,244.495200
XS GIS Cut Line= 6
 658666.98739275731577.294712428658457.359688771731490.074403627
658354.127970016731453.138245926658311.489309795731443.051707225
658267.686191181731438.142524873658141.896364715731434.751151501
#Sta/Elev= 30
9546.683219.70799559.439 215.4199581.029210.40589606.334209.82949624.425212.2688
9646.124206.86469667.822203.78449700.369 202.5679754.614198.48069765.463198.7286
9797.742195.64029819.201197.13369850.963191.5867    9872191.28729882.518192.6852
9903.091191.41129923.643191.97529943.843193.64489963.968188.31199974.014182.5213
9994.014178.567410004.02177.682710014.02180.761110024.02187.773310034.02202.4099
10044.03214.304710054.04222.801710074.06241.8644 10084.1247.457110097.26247.2961
#Mann= 3 , 0 , 0
9546.683    0.04       09546.683    0.04       010097.26    0.04       0
#XS Ineff= 2 , 0
       09848.148                       0
Bank Sta=9546.683,10097.26
Exp/Cntr=0.3,0.1

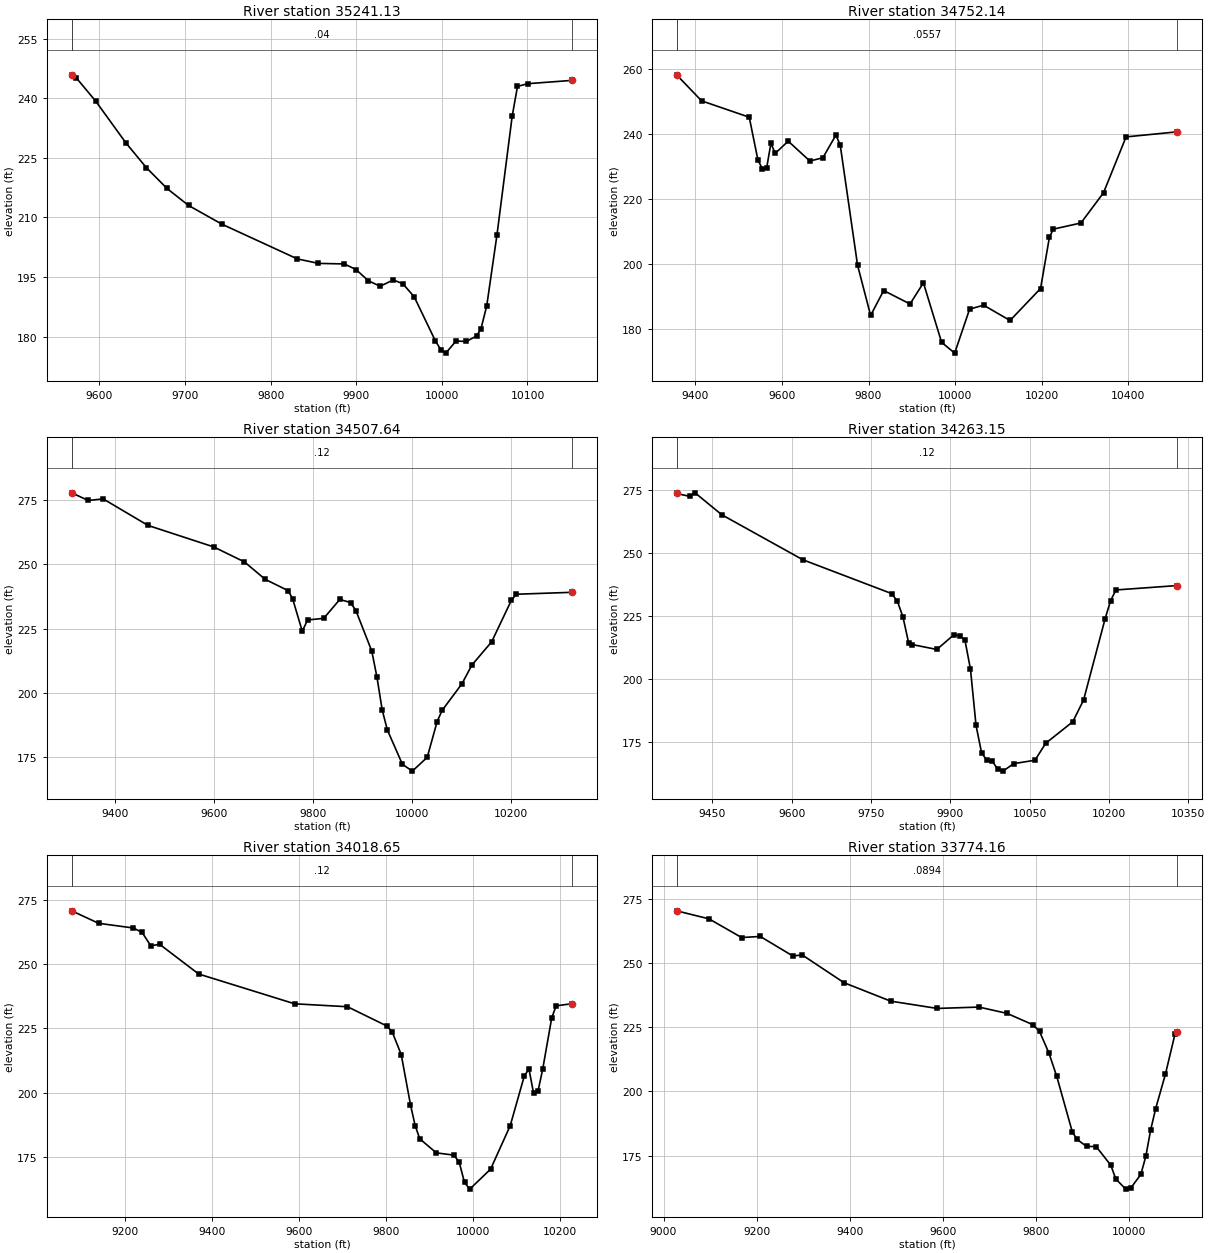
Type RM Length L Ch R = 1 ,35241.13,488.990400,488.990400,488.990400
XS GIS Cut Line= 6
658699.591472799731514.759017915658611.869897762731461.400663838
658548.811216719  731411.1124921658430.937908465731290.267970514
658394.381378857731258.404769034 658240.86655575731157.350324645
#Sta/Elev= 30
9567.758245.89229572.972245.16629595.679239.29629630.979228.77989654.848222.5491
9679.072217.27859704.168213.01319743.158 208.2949831.186199.56089855.756198.4239
9886.105198.28379899.834196.86259914.133194.06039927.938192.66479943.298194.2528
9954.469193.29789967.734190.01069992.366178.9551    9999176.6185 10004.6175.8311
10016.59 178.88110028.54 178.762 10040.5180.152110045.62181.883410052.46187.7747
10064.41205.6452 10082.1235.402610088.33242.970810100.29243.663510152.39244.4988
#Mann= 3 , 0 , 0
9567.758    0.04       09567.758    0.04       010152.39    0.04       0
#XS Ineff= 2 , 0
       0                               0
Bank Sta=9567.758,10152.39
Exp/Cntr=0.3,0.1

Type RM Length L Ch R = 1 ,34752.14,244.495200,244.495200,244.495200
XS GIS Cut Line= 6
659352.693035655730938.325166056659032.353585189730931.043889089
 658876.62509127730942.098852588658605.307583249731018.035784095
658497.940399192731005.495749671658220.445524948730928.889975332
#Sta/Elev= 30
9356.661258.19799414.425250.18859524.516245.1458 9544.52231.97679554.522229.3328
9564.524229.38549574.526237.10489584.526234.02399614.527237.77629664.528231.6618
9694.547232.66029724.579239.62489734.589236.62029774.696199.55749804.837184.1111
9834.993191.78929895.848187.64159926.791194.15189968.775175.8428    9999172.5131
10033.48186.066810065.88187.270410126.85182.559710197.34192.406810217.81208.1881
10226.79210.687810290.64212.580210342.77221.891910394.87239.088710512.98240.6477
#Mann= 3 , 0 , 0
9356.661  0.0557       09356.661  0.0557       010512.98  0.0557       0
#XS Ineff= 2 , 0
       0 9919.64                       0
Bank Sta=9356.661,10512.98
Exp/Cntr=0.3,0.1

Type RM Length L Ch R = 1 ,34507.64,244.495200,244.495200,244.495200
XS GIS Cut Line= 6
659198.446241456730664.579353042 659073.38705413730677.068846663
658903.239946031730711.376060162658552.823740966730835.369204767
658389.028545256730849.855039866658211.898225703 730843.96071214
#Sta/Elev= 30
9311.504277.85949345.021 274.8819375.212275.5023    9466 265.1849598.801256.8346
9661.241250.98939703.385   244.29749.592239.82699758.718236.71419778.332224.0397
9789.196 228.412 9821.79229.03529854.384 236.3929876.113235.17669886.978232.0481
9919.121216.28499929.644 206.1029940.167193.41299950.666185.59979981.165172.2637
10001.24169.610310031.37174.980310051.45 188.90110061.49193.227910101.66203.5894
10121.74210.856410161.85219.923210201.85  236.0910211.85238.414910325.17239.1676
#Mann= 3 , 0 , 0
9311.504    0.12       09311.504    0.12       010325.17    0.12       0
#XS Ineff= 2 , 0
       0                               0
Bank Sta=9311.504,10325.17
Exp/Cntr=0.3,0.1

Type RM Length L Ch R = 1 ,34263.15,244.495100,244.495100,244.495100
XS GIS Cut Line= 6
659099.643259427730467.822066238658922.256125251730496.073680525
658824.471187242730521.120391704658542.153465412730619.606039761
658455.062764887730617.552441427658180.458554095730667.299700265
#Sta/Elev= 30
 9382.55273.47889407.405272.33999417.492273.74089467.923265.05619621.352247.1871
9789.223233.76819799.901230.82129810.578224.54869821.255214.32679828.611213.5259
9874.643211.60359906.675217.37749918.449217.05849927.853215.28569938.333203.7428
9948.814181.47149959.294 170.6229969.476 167.564 9979.54167.32939989.628164.1297
 9999.74163.335110020.01   166.310060.24167.660310080.66174.404410131.71182.9084
10152.13191.517510192.97223.825810203.18230.921510213.39235.207410329.24236.9536
#Mann= 3 , 0 , 0
 9382.55    0.12       0 9382.55    0.12       010329.24    0.12       0
#XS Ineff= 2 , 0
       0                               0
Bank Sta=9382.55,10329.24
Exp/Cntr=0.3,0.1

Type RM Length L Ch R = 1 ,34018.65,244.495200,244.495200,244.495200
XS GIS Cut Line= 6
659296.962519715730270.685495545658884.011367037730274.338446695
658625.897080173730312.139136509658489.916334403730354.749228371
658316.823518622 730456.29553173658188.686552652730494.130816746
#Sta/Elev= 30
9076.916270.6834 9138.94 265.8339218.996264.00849238.999262.26929258.999257.0598
    9279 257.7089369.046246.13479589.851234.55859711.491233.42079801.673225.9718
9814.234223.69799835.088214.84779856.455195.34579867.139187.24769877.822182.0985
9915.815176.64179956.527175.75689968.638172.94929980.748165.12919992.859162.5513
10040.75170.319110085.89187.193210118.34206.527610129.05209.216410139.68199.7893
10150.12200.851810160.55  209.06 10181.4229.085410191.64233.777210228.83234.6122
#Mann= 3 , 0 , 0
9076.916    0.12       09076.916    0.12       010228.83    0.12       0
#XS Ineff= 2 , 0
       0                               0
Bank Sta=9076.916,10228.83
Exp/Cntr=0.3,0.1

Type RM Length L Ch R = 1 ,33774.16,244.495200,244.495200,244.495200
XS GIS Cut Line= 6
659354.364656418730229.899766828659126.774473142730214.002387832
658631.976075128730221.027919196658538.139852301730217.212702207
 658457.53141978730202.157661214658290.637544314730143.814783924
#Sta/Elev= 30
9028.063 270.2649097.721 267.1439167.876 259.872 9207.94260.29779278.019  252.68
9298.021253.1047 9388.03242.28869488.059235.13159588.101232.28199678.138232.8086
9738.164  230.379794.208225.92339808.201223.32049828.243214.99889845.139205.8899
9878.598184.29199888.779181.32859909.297178.58829929.881178.53629961.436171.2813
9972.104165.91579993.632161.967810004.43162.4201   10026167.689210036.61174.6932
10047.22185.119510057.82 193.28710078.79 206.68810099.61222.478210104.15223.2415
#Mann= 3 , 0 , 0
9028.063  0.0894       09028.063  0.0894       010104.15  0.0894       0
#XS Ineff= 2 , 0
       0                               0
Bank Sta=9028.063,10104.15
Exp/Cntr=0.3,0.1

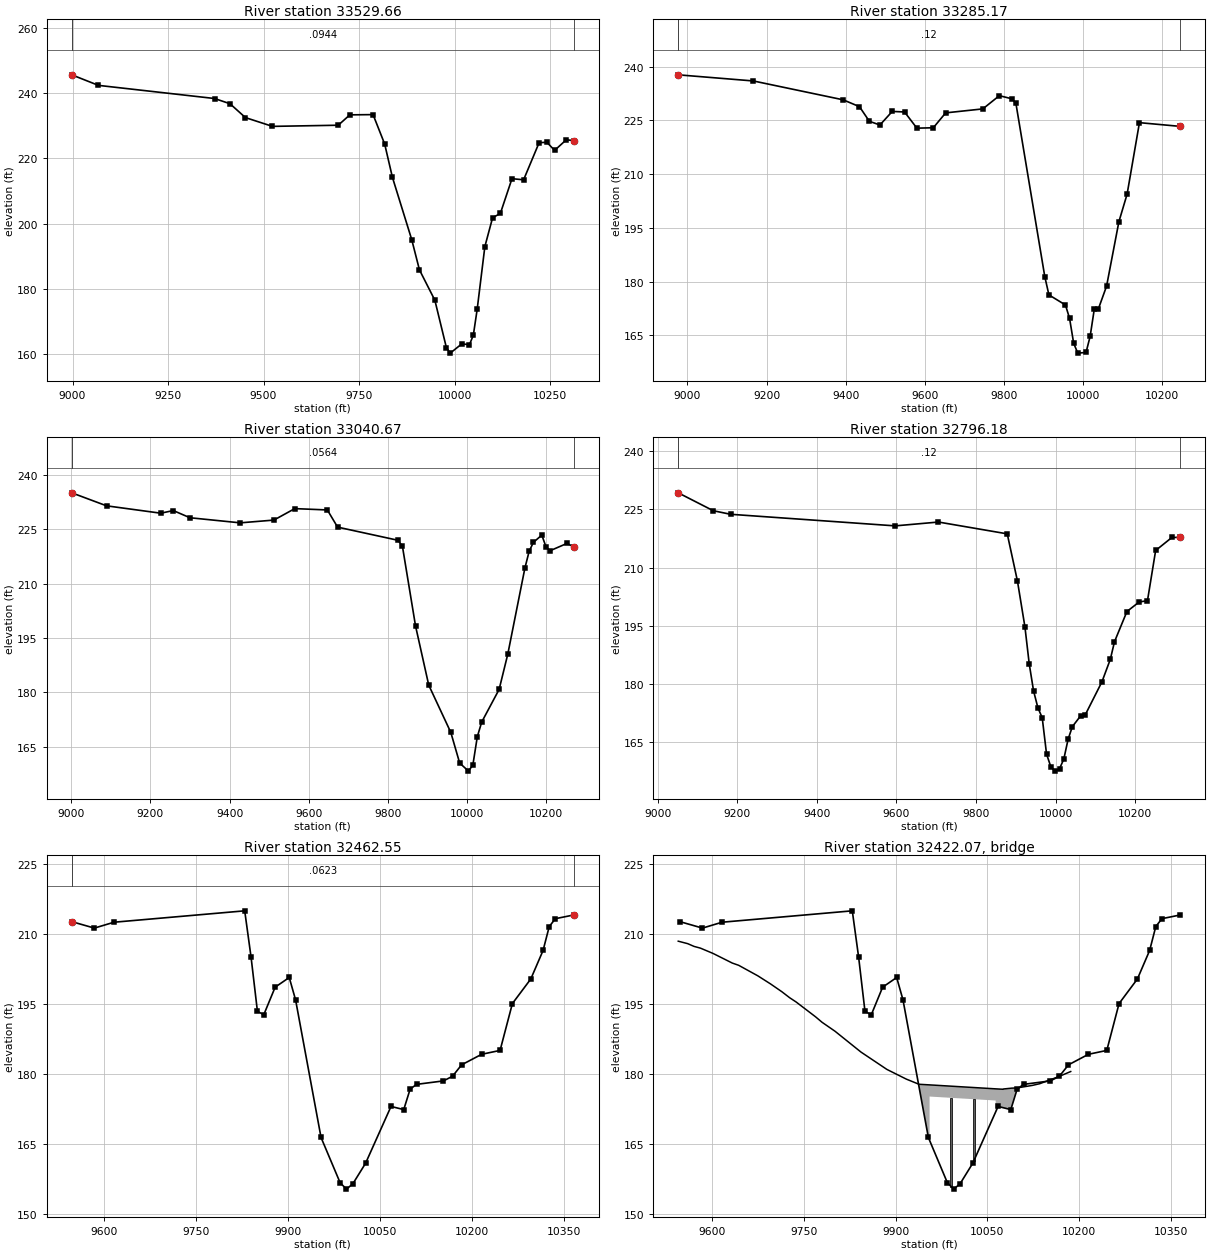
Type RM Length L Ch R = 1 ,33529.66,244.495200,244.495200,244.495200
XS GIS Cut Line= 6
659443.822216228 730097.48323805659221.332134224730059.244928085
658849.545575221730002.901222194658593.639548168729961.300821392
658366.795149658 729932.84372187658145.401139685729894.523164716
#Sta/Elev= 30
8998.047245.57329067.878242.34529371.802238.32479412.259236.72449452.716232.4776
9523.515229.79549695.618230.14699726.011233.32299786.799 233.3969817.193 224.392
9837.455214.20929888.025195.12829908.226185.87749948.571176.58079978.754162.0754
9988.815160.391810019.02163.211710039.17162.998810049.25165.863810059.32173.7689
10079.47193.001910099.71201.8457   10120203.135410150.45213.7874 10180.9213.4445
10221.49224.804210241.79224.926510262.09  222.4510292.53225.677410312.42225.4602
#Mann= 3 , 0 , 0
8998.047  0.0944       08998.047  0.0944       010312.42  0.0944       0
#XS Ineff= 2 , 0
       0                               0
Bank Sta=8998.047,10312.42
Exp/Cntr=0.3,0.1

Type RM Length L Ch R = 1 ,33285.17,244.495200,244.495200,244.495200
XS GIS Cut Line= 6
659479.305883628 729974.09684914659003.437729292729853.074886883
658841.265532289729807.653881179658505.101314483729706.182210314
 658333.00970494729657.526265875658254.909746155 729637.89792974
#Sta/Elev= 30
8976.683 237.7319166.717236.01819393.762230.75479435.092228.83749460.052224.7581
 9486.85223.72029518.005 227.5119549.159227.35689580.314222.83349621.853222.9488
9653.106227.10699747.117228.2162  9788.9231.90999820.237231.04859830.682229.8402
9903.802181.39879914.247176.2736 9956.03173.45939966.476169.73979976.921162.7346
9987.366160.005510008.16 160.19910018.55164.680810028.95172.220310039.34172.3447
10060.12178.716410091.29196.715710112.07204.417910143.25 224.37310246.63223.3297
#Mann= 3 , 0 , 0
8976.683    0.12       08976.683    0.12       010246.63    0.12       0
#XS Ineff= 2 , 0
       0                               0
Bank Sta=8976.683,10246.63
Exp/Cntr=0.3,0.1

Type RM Length L Ch R = 1 ,33040.67,244.495200,244.495200,244.495200
XS GIS Cut Line= 6
659518.473375628729837.900797413659181.342048528729726.248546325
658952.666175577729642.619578907658773.435922844729567.557366649
658482.345022174729428.934898713658338.032915623729378.102794423
#Sta/Elev= 30
9001.195235.06999089.127231.48149226.071229.44549257.674230.1759 9299.81228.1907
9426.711 226.7849511.883227.54519564.626 230.7129646.883230.3413 9672.81225.6018
9825.556221.96519836.596220.31459869.715198.32489903.058 181.9919958.889168.9152
9981.221160.474110003.54158.240910014.65159.963710025.75167.716610036.86171.7784
10080.94180.811310102.79190.524410146.02214.292910156.78218.935510167.53221.3973
10188.76223.403610199.36220.141910209.96 219.10210251.97221.0863 10269.7220.2008
#Mann= 3 , 0 , 0
9001.195  0.0564       09001.195  0.0564       0 10269.7  0.0564       0
#XS Ineff= 2 , 0
       0                               0
Bank Sta=9001.195,10269.7
Exp/Cntr=0.3,0.1

Type RM Length L Ch R = 1 ,32796.18,333.629200,333.629200,333.629200
XS GIS Cut Line= 6
659565.929011123729629.883019222658671.954582221729248.411186991
658619.531011535729228.449572212658517.246408963729196.314594856
658457.991897151729181.688323216658394.263248577729168.800999553
#Sta/Elev= 30
9051.909229.23959139.986224.63059183.519223.71619597.011220.73619705.638221.7218
9878.477218.68139904.082206.54799922.893194.73969933.756185.17799944.618178.2512
9955.481173.92029966.344171.34979977.206162.01679988.069158.70269998.932157.6202
10009.76158.235610020.58160.719810031.32 165.81210042.02169.069210063.42171.9221
10074.12172.041810116.38180.608310137.46  186.4110147.91 190.92110179.14198.6958
10210.12201.165610230.72201.467310251.29214.3979 10292.1217.754410313.26217.7765
#Mann= 3 , 0 , 0
9051.909    0.12       09051.909    0.12       010313.26    0.12       0
#XS Ineff= 2 , 0
       0                               0
Bank Sta=9051.909,10313.26
Exp/Cntr=0.3,0.1

Type RM Length L Ch R = 1 ,32462.55,75.167600,75.167600,75.167600
XS GIS Cut Line= 5
659189.540466418728795.396505887658936.334340632728888.931604579
658655.233676612728965.248526946658581.460651666729032.661808372
658424.939753081729038.590630286
#Sta/Elev= 30
9547.594212.64489584.416211.26469616.397212.52299829.269214.96539839.631205.0404
9849.993193.42499860.355192.70169878.852198.60329901.803200.67919912.165195.8657
9953.613166.39419984.699156.69449995.061155.330410005.42 156.47510026.15160.8761
10067.59173.050710088.32172.373410098.68176.748110109.12177.7801 10152.9178.5201
10167.73179.512310182.55181.9622 10215.2184.222410245.22185.053810265.24195.0882
10295.26200.366310315.27206.483310325.28211.593310335.29213.282810365.37214.0826
#Mann= 3 , 0 , 0
9547.594  0.0623       09547.594  0.0623       010365.37  0.0623       0
#XS Ineff= 2 , 0
       0                               0
Bank Sta=9547.594,10365.37
Exp/Cntr=0.3,0.1

Type RM Length L Ch R = 3 ,32422.07,,,
BEGIN DESCRIPTION:
END DESCRIPTION:
Bridge Culvert--1,0,-1,-1, 0
Deck Dist Width WeirC Skew NumUp NumDn MinLoCord MaxHiCord MaxSubmerge Is_Ogee
23.583800,28.000000,2.6,0, 31, 31, , , 0.95, 0, 0,0,,
 9544.81 9560.27 9570.69 9581.10 9601.94 9633.19 9643.60 9674.85 9695.69 9714.26
 9726.94 9737.49 9769.28 9779.88 9801.07 9843.46 9885.85 9917.64 9938.32 9955.58
 9955.5810063.5810063.5810075.8210076.3110089.8610098.7010123.3310135.6410166.05
10186.26
  208.46  207.93  207.34  206.97  205.82  203.77  203.29  201.04  199.30  197.62
  196.34  195.43  192.25  191.08  189.16  184.70  180.98  178.90  177.80  177.67
  177.67  176.82  176.82  176.73  176.79  176.97  177.02  177.55  177.92  179.41
  180.53
 -791.54 -792.07 -792.66 -793.03 -794.18 -796.23 -796.71 -798.96 -800.70 -802.38
 -803.66 -804.57 -807.75 -808.92 -810.84 -815.30 -819.02 -821.10 -822.20 -822.33
  175.17  174.32 -823.18 -823.27 -823.21 -823.03 -822.98 -822.45 -822.08 -820.59
 -819.47
 9544.81 9560.27 9570.69 9581.10 9601.94 9633.19 9643.60 9674.85 9695.69 9714.26
 9726.94 9737.49 9769.28 9779.88 9801.07 9843.46 9885.85 9917.64 9938.32 9950.11
 9950.1110058.1110058.1110075.8210076.3110089.8610098.7010123.3310135.6410166.05
10186.26
  208.46  207.93  207.34  206.97  205.82  203.77  203.29  201.04  199.30  197.62
  196.34  195.43  192.25  191.08  189.16  184.70  180.98  178.90  177.80  177.71
  177.71  176.87  176.87  176.73  176.79  176.97  177.02  177.55  177.92  179.41
  180.53
 -791.54 -792.07 -792.66 -793.03 -794.18 -796.23 -796.71 -798.96 -800.70 -802.38
 -803.66 -804.57 -807.75 -808.92 -810.84 -815.30 -819.02 -821.10 -822.20 -822.29
  175.21  174.37 -823.13 -823.27 -823.21 -823.03 -822.98 -822.45 -822.08 -820.59
 -819.47
Pier Skew, UpSta & Num, DnSta & Num=  ,9991.08, 2 ,9985.61, 2 , 0 , 0 , 0 ,,
    3.00    3.00
 -822.61  177.39
    3.00    3.00
 -822.57  177.43
Pier Skew, UpSta & Num, DnSta & Num=  ,10028.08, 2 ,10022.61, 2 , 0 , 0 , 0 ,,
    3.00    3.00
 -822.90  177.10
    3.00    3.00
 -822.86  177.14
BR Coef=-1 , 0 , 0 ,, 0 ,,,0.8,0,1,0,
WSPro=,,,, 1 ,,,, 0 ,,,, 0 ,,,,-1 ,-1 ,-1 , 0 , 0 , 0 , 0 , 0
BC Design=,, 0 ,, 0 ,,,,,,