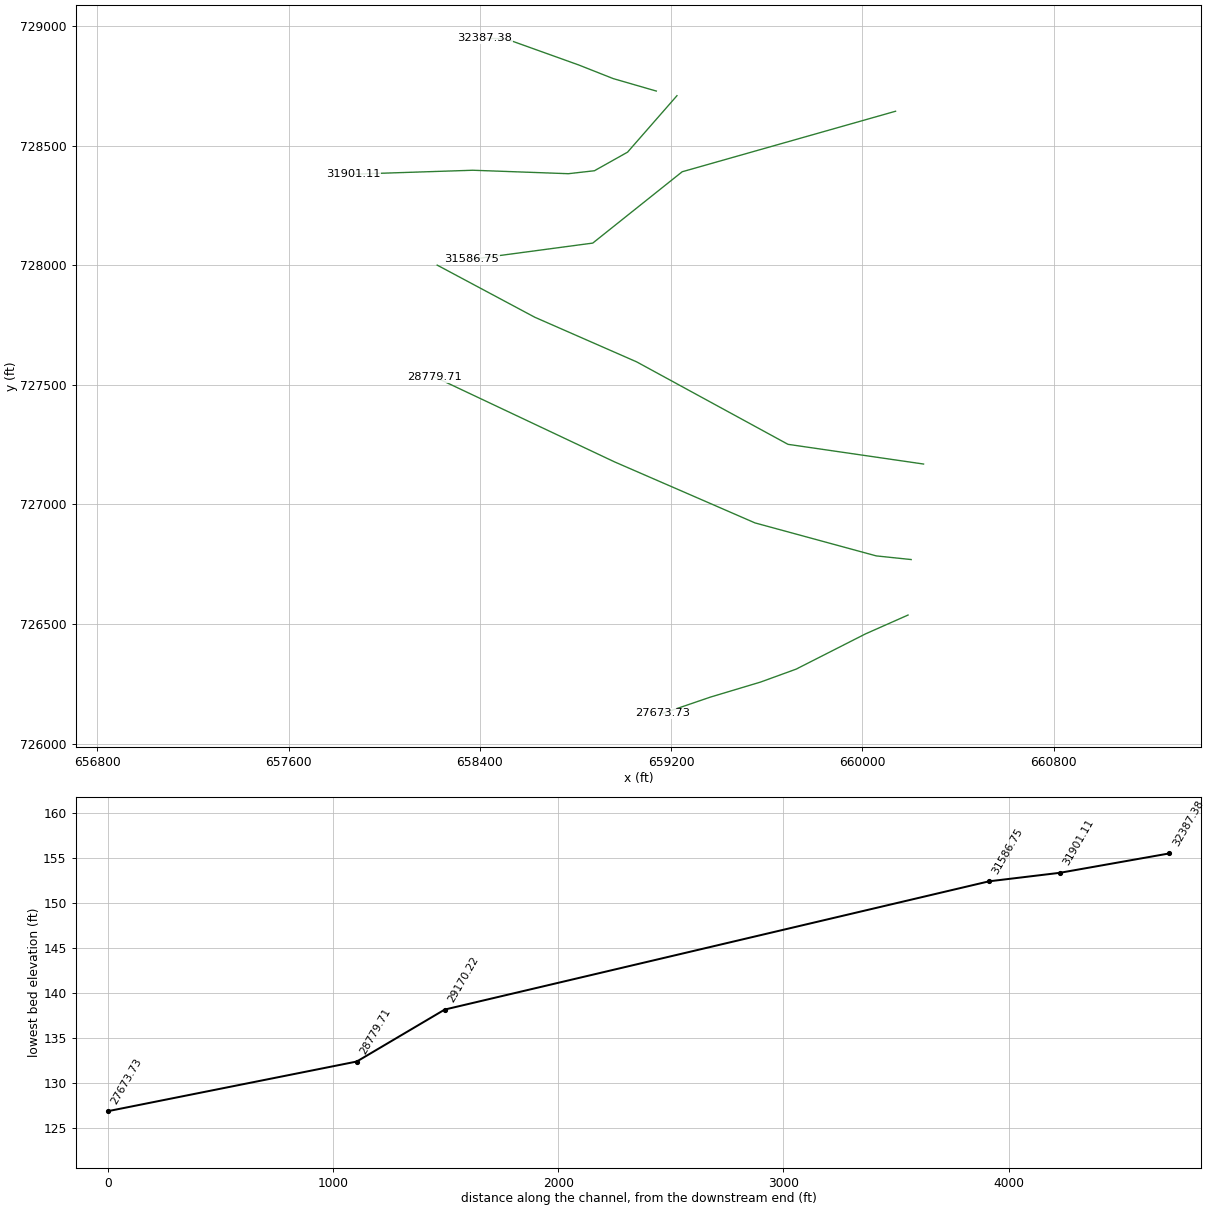
HEC-RAS study 4379_ras.prj: 4379

--- 4379_ras.g01 (geometry) --- (continued)

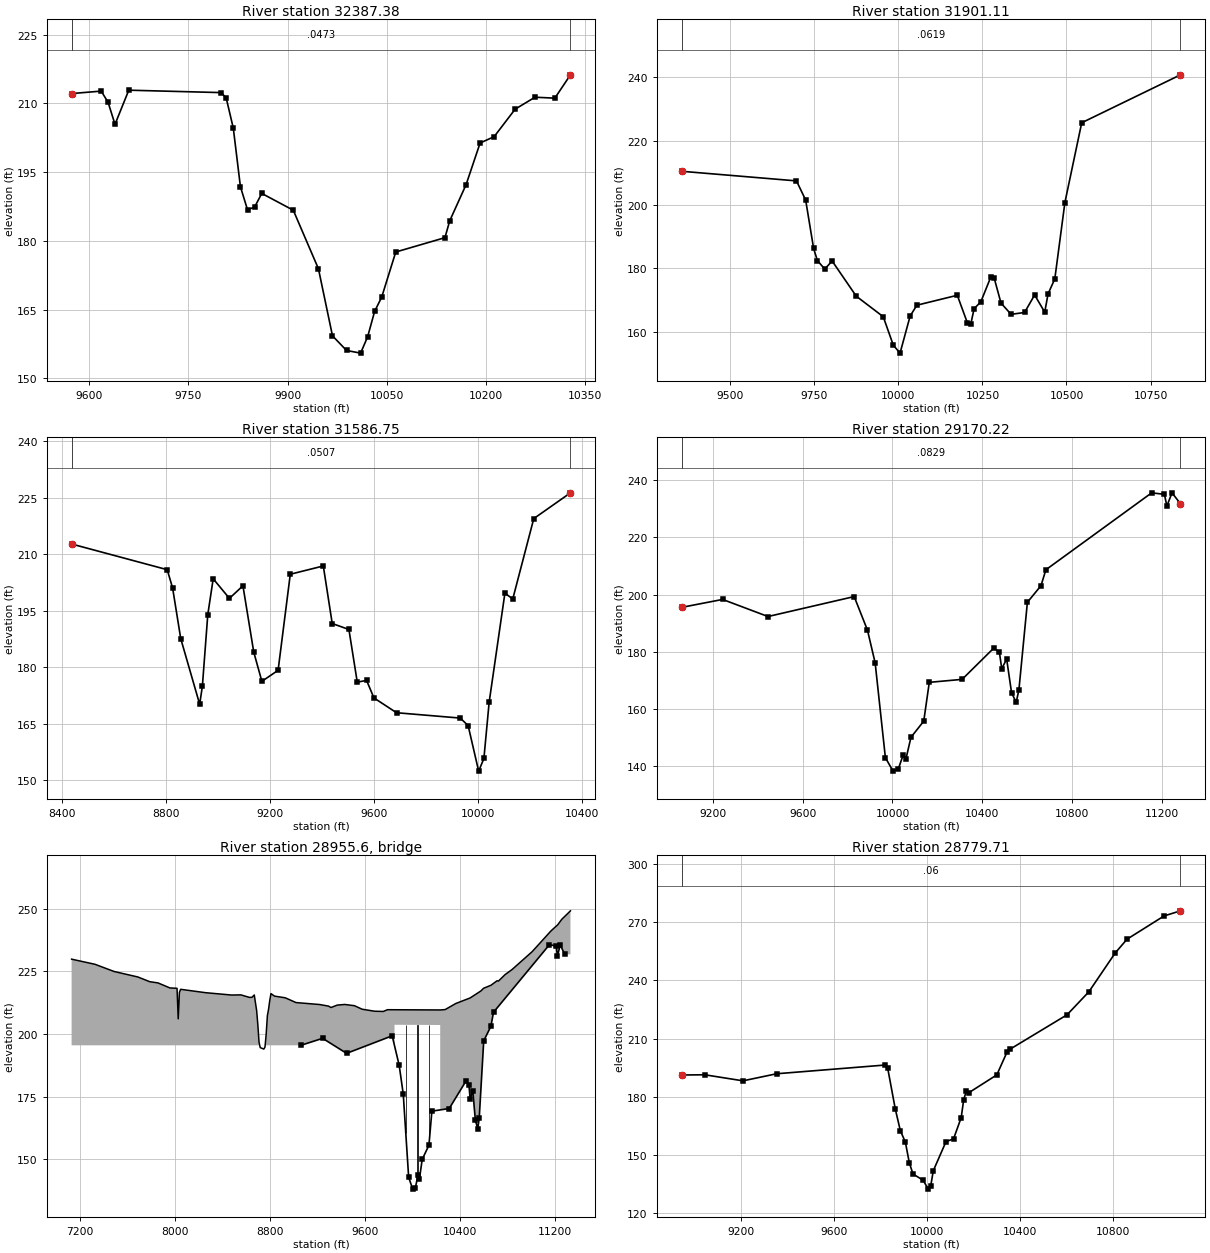
Type RM Length L Ch R = 1 ,32387.38,486.275800,486.275800,486.275800
XS GIS Cut Line= 5
659137.999092708 728728.74817783658957.957468629 728780.81596458
658812.955316186728838.053656355658507.687626719728947.441245064
658421.412114936728949.223796958
#Sta/Elev= 30
9573.701  212.149618.463212.67179628.872210.20639639.282205.42029660.102212.8738
9799.752 212.3469807.304211.18429818.055204.58699828.806191.81739839.557186.7661
9850.308187.37769861.058 190.3459908.694186.68029946.707173.90469967.952159.2631
9989.198156.070310010.44155.492210021.07159.061210031.69164.624910042.31167.7087
10063.56177.558710137.91180.690610145.12184.366910169.78192.230910191.03201.3491
10212.27202.732810243.97208.729610273.98211.339410303.99211.135610327.58216.2256
#Mann= 3 , 0 , 0
9573.701  0.0473       09573.701  0.0473       010327.58  0.0473       0
#XS Ineff= 2 , 0
       0                               0
Bank Sta=9573.701,10327.58
Exp/Cntr=0.3,0.1

Type RM Length L Ch R = 1 ,31901.11,314.352000,314.352000,314.352000
XS GIS Cut Line= 6
659224.354030403 728709.35359485659017.810639418728473.235594264
658879.314232797 728395.53852492 658770.31378155728383.153729753
658370.971975464 728397.57694707657871.630776274728381.226590852
#Sta/Elev= 30
9355.395210.4478 9697.01207.42749724.322201.39889747.964186.20049759.202182.3921
9781.268179.71989802.874182.29649874.768171.22049954.988164.77629984.993155.8268
10005.02 153.33810035.06165.005110055.08 168.38910175.24171.507810205.25162.8492
10215.25162.398210225.26167.285210245.26169.444810275.27177.330410285.27176.7937
10305.28169.051610335.29165.520510375.29166.102310405.29171.605510435.29166.2052
10445.29171.960210465.29176.654810495.29200.6393 10545.3225.684610839.04240.7377
#Mann= 3 , 0 , 0
9355.395  0.0619       09355.395  0.0619       010839.04  0.0619       0
#XS Ineff= 2 , 0
       0                10068.88       0
Bank Sta=9355.395,10839.04
Exp/Cntr=0.3,0.1

Type RM Length L Ch R = 1 ,31586.75,2416.532400,2416.532400,2416.532400
XS GIS Cut Line= 4
660138.537880003728644.352092698659246.189209968728391.249595448
 658872.22501719728092.968632177658365.232598007 728025.21388489
#Sta/Elev= 30
8436.502212.67548803.985205.86048824.774 200.9798855.958187.56838928.719170.1427
8939.113174.93358959.902193.91778980.691203.44379043.058198.2441 9095.03201.5927
9136.608 183.9819167.792  176.229230.159179.15079277.012204.65199403.946 206.847
9438.221191.57119502.369189.98939534.443176.00529570.234176.4751 9598.59 171.822
9685.356167.89639930.403166.4735 9960.67164.464110001.03152.3936 10021.2155.7482
10041.38170.673110101.91199.623710132.18198.090510212.89219.4211 10353.9226.2612
#Mann= 3 , 0 , 0
8436.502  0.0507       08436.502  0.0507       0 10353.9  0.0507       0
#XS Ineff= 2 , 0
       09339.454        10201.38       0
Bank Sta=8436.502,10353.9
Exp/Cntr=0.3,0.1

Type RM Length L Ch R = 1 ,29170.22,390.510300,390.510300,390.510300
XS GIS Cut Line= 5
 660255.58702492 727169.00099075659688.784204721727251.385121599
659055.892790586727596.229802385658629.908184886727782.851629645
658221.722705493728000.814749721
#Sta/Elev= 30
9061.011195.51839243.496198.29999445.597192.3108 9829.43 199.3049888.617187.5077
9922.782176.05929968.334142.8659 10002.5138.153210025.27138.781510048.05143.9352
10059.44142.267310082.21150.002310139.16155.671810163.84169.258210309.98170.2997
10451.13181.264110476.05179.7775 10486.5174.012910508.33177.430910530.17165.5987
10550.81162.245310562.92166.638210600.65 197.29910661.18203.119110683.01208.6954
 11153.9 235.63611210.58235.133511221.92231.033211244.59235.647811282.32231.8275
#Mann= 3 , 0 , 0
9061.011  0.0829       09061.011  0.0829       011282.32  0.0829       0
#XS Ineff= 2 , 0
       09731.183         10297.7       0
Bank Sta=9061.011,11282.32
Exp/Cntr=0.3,0.1

Type RM Length L Ch R = 3 , 28955.6,,,
BEGIN DESCRIPTION:
END DESCRIPTION:
Bridge Culvert--1,0,-1,-1, 0
Deck Dist Width WeirC Skew NumUp NumDn MinLoCord MaxHiCord MaxSubmerge Is_Ogee
125.255150,140.000000,2.6,0, 60, 60, , , 0.95, 0, 0,0,,
 7129.26 7326.60 7486.82 7687.08 7787.14 7857.18 7957.24 8017.27 8027.28 8037.28
 8047.29 8257.41 8477.54 8554.61 8627.82 8647.89 8667.95 8688.02 8698.05 8708.09
 8718.12 8748.22 8758.25 8768.28 8778.32 8788.35 8798.38 8808.42 8838.51 8928.81
 9019.11 9220.18 9293.47 9314.41 9366.76 9429.57 9511.74 9576.15 9680.61 9754.13
 9789.94 9848.98 9848.9810233.9810233.9810275.7110364.9410486.0010576.2910599.36
10661.5010712.9410724.7810781.0810837.8711008.2411167.2411224.0311258.1011331.17
  229.88  227.83  224.97  222.78  220.90  220.40  218.41  218.25  206.08  216.60
  217.86  216.51  215.57  215.64  214.63  214.66  215.59  209.33  203.63  196.74
  194.60  194.01  194.85  200.05  207.35  209.95  213.41  216.14  215.14  214.47
  212.57  211.78  211.15  210.59  211.56  211.81  211.32  209.92  209.12  209.02
  209.72  209.71  209.71  209.62  209.62  209.77  212.19  214.41  217.19  218.27
  219.47  221.26  221.14  223.75  225.69  232.86  241.16  243.60  245.78  249.16
 -770.12 -772.17 -775.03 -777.22 -779.10 -779.60 -781.59 -781.75 -793.92 -783.40
 -782.14 -783.49 -784.43 -784.36 -785.37 -785.34 -784.41 -790.67 -796.37 -803.26
 -805.40 -805.99 -805.15 -799.95 -792.65 -790.05 -786.59 -783.86 -784.86 -785.53
 -787.43 -788.22 -788.85 -789.41 -788.44 -788.19 -788.68 -790.08 -790.88 -790.98
 -790.28 -790.29  203.71  203.62 -790.38 -790.23 -787.81 -785.59 -782.81 -781.73
 -780.53 -778.74 -778.86 -776.25 -774.31 -767.14 -758.84 -756.40 -754.22 -750.84
 7129.26 7326.60 7486.82 7687.08 7787.14 7857.18 7957.24 8017.27 8027.28 8037.28
 8047.29 8257.41 8477.54 8554.61 8627.82 8647.89 8667.95 8688.02 8698.05 8708.09
 8718.12 8748.22 8758.25 8768.28 8778.32 8788.35 8798.38 8808.42 8838.51 8928.81
 9019.11 9220.18 9293.47 9314.41 9366.76 9429.57 9511.74 9576.15 9680.61 9754.13
 9789.94 9848.96 9848.9610233.9610233.9610275.7110364.9410486.0010576.2910599.36
10661.5010712.9410724.7810781.0810837.8711008.2411167.2411224.0311258.1011331.17
  229.88  227.83  224.97  222.78  220.90  220.40  218.41  218.25  206.08  216.60
  217.86  216.51  215.57  215.64  214.63  214.66  215.59  209.33  203.63  196.74
  194.60  194.01  194.85  200.05  207.35  209.95  213.41  216.14  215.14  214.47
  212.57  211.78  211.15  210.59  211.56  211.81  211.32  209.92  209.12  209.02
  209.72  209.71  209.71  209.62  209.62  209.77  212.19  214.41  217.19  218.27
  219.47  221.26  221.14  223.75  225.69  232.86  241.16  243.60  245.78  249.16
 -770.12 -772.17 -775.03 -777.22 -779.10 -779.60 -781.59 -781.75 -793.92 -783.40
 -782.14 -783.49 -784.43 -784.36 -785.37 -785.34 -784.41 -790.67 -796.37 -803.26
 -805.40 -805.99 -805.15 -799.95 -792.65 -790.05 -786.59 -783.86 -784.86 -785.53
 -787.43 -788.22 -788.85 -789.41 -788.44 -788.19 -788.68 -790.08 -790.88 -790.98
 -790.28 -790.29  203.71  203.62 -790.38 -790.23 -787.81 -785.59 -782.81 -781.73
 -780.53 -778.74 -778.86 -776.25 -774.31 -767.14 -758.84 -756.40 -754.22 -750.84
Pier Skew, UpSta & Num, DnSta & Num=  ,9944.23, 2 ,9944.21, 2 , 0 , 0 , 0 ,,
    4.00    4.00
 -790.31  209.69
    4.00    4.00
 -790.31  209.69
Pier Skew, UpSta & Num, DnSta & Num=  ,10041.48, 2 ,10041.46, 2 , 0 , 0 , 0 ,,
    4.00    4.00
 -790.33  209.67
    4.00    4.00
 -790.33  209.67
Pier Skew, UpSta & Num, DnSta & Num=  ,10138.73, 2 ,10138.71, 2 , 0 , 0 , 0 ,,
    4.00    4.00
 -790.36  209.64
    4.00    4.00
 -790.36  209.64
BR Coef=-1 , 0 , 0 ,, 0 ,,,0.8,0,1,0,
WSPro=,,,, 1 ,,,, 0 ,,,, 0 ,,,,-1 ,-1 ,-1 , 0 , 0 , 0 , 0 , 0
BC Design=,, 0 ,, 0 ,,,,,,

Type RM Length L Ch R = 1 ,28779.71,1105.980000,1105.980000,1105.980000
XS GIS Cut Line= 5
660203.810150251726769.579386189660057.970862985726784.830553487
659550.846332401726922.768425792658962.581876993727178.359189212
658210.996095351727533.168720603
#Sta/Elev= 30
8943.915191.24789043.264 191.3649207.625188.24369352.712 191.8929818.729196.3881
9829.632194.93679862.342173.81059884.148162.59459905.954156.58249922.832145.9509
9938.663140.19049982.276136.959510004.08132.382310014.99134.126710025.89141.8575
 10080.4156.839510113.11158.343310145.82169.249210156.73178.567310167.63182.8617
10178.53182.098810299.05191.312310343.28203.183910354.34204.445410600.99222.3086
10694.69234.155410807.73254.141110858.66261.275911017.84273.272111088.62275.9275
#Mann= 3 , 0 , 0
8943.915    0.06       08943.915    0.06       011088.62    0.06       0
#XS Ineff= 2 , 0
       0 9712.06        10318.96       0
Bank Sta=8943.915,11088.62
Exp/Cntr=0.3,0.1

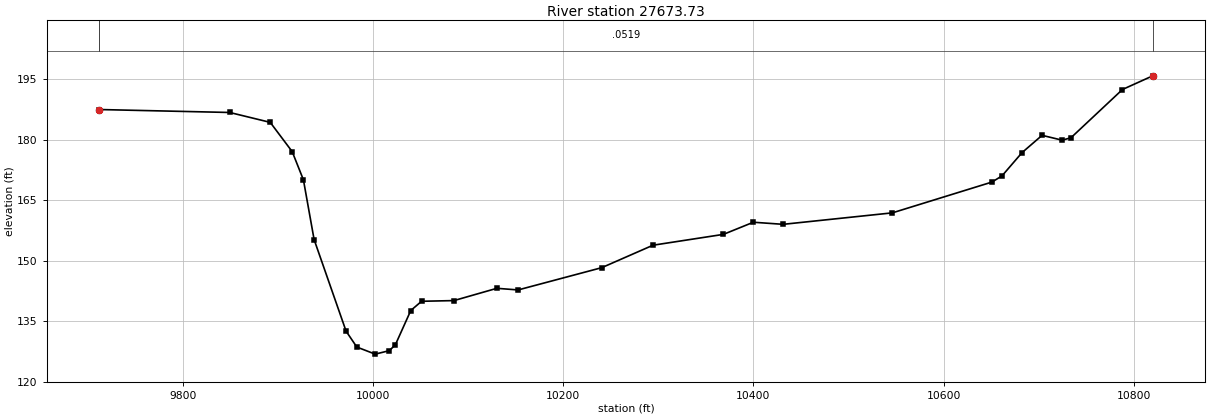
Type RM Length L Ch R = 1 ,27673.73,647.584100,647.584100,647.584100
XS GIS Cut Line= 6
660190.769864863726537.542859036660012.550750957726458.560814548
659722.810442027726311.340681649659574.348869629726257.341685149
659364.490147636726194.409032061 659165.10319183726126.296474495
#Sta/Elev= 30
9712.048   187.59849.156186.76939891.785184.31869914.895177.06029926.705170.0582
9937.918155.27739971.558132.55329982.843128.619210002.16126.863110016.89127.7179
10023.31129.1321 10039.6137.676110050.95139.9645   10085140.136510130.14 143.179
10152.46142.776510240.53 148.30410294.35153.862910368.35156.546610399.91 159.559
10431.23159.041610546.07 161.88410650.87169.520710661.41171.050210682.49176.8176
10703.57181.105410724.65179.903810733.93180.501110788.09192.464410819.96195.8557
#Mann= 3 , 0 , 0
9712.048  0.0519       09712.048  0.0519       010819.96  0.0519       0
#XS Ineff= 2 , 0
       0                               0
Bank Sta=9712.048,10819.96
Exp/Cntr=0.3,0.1