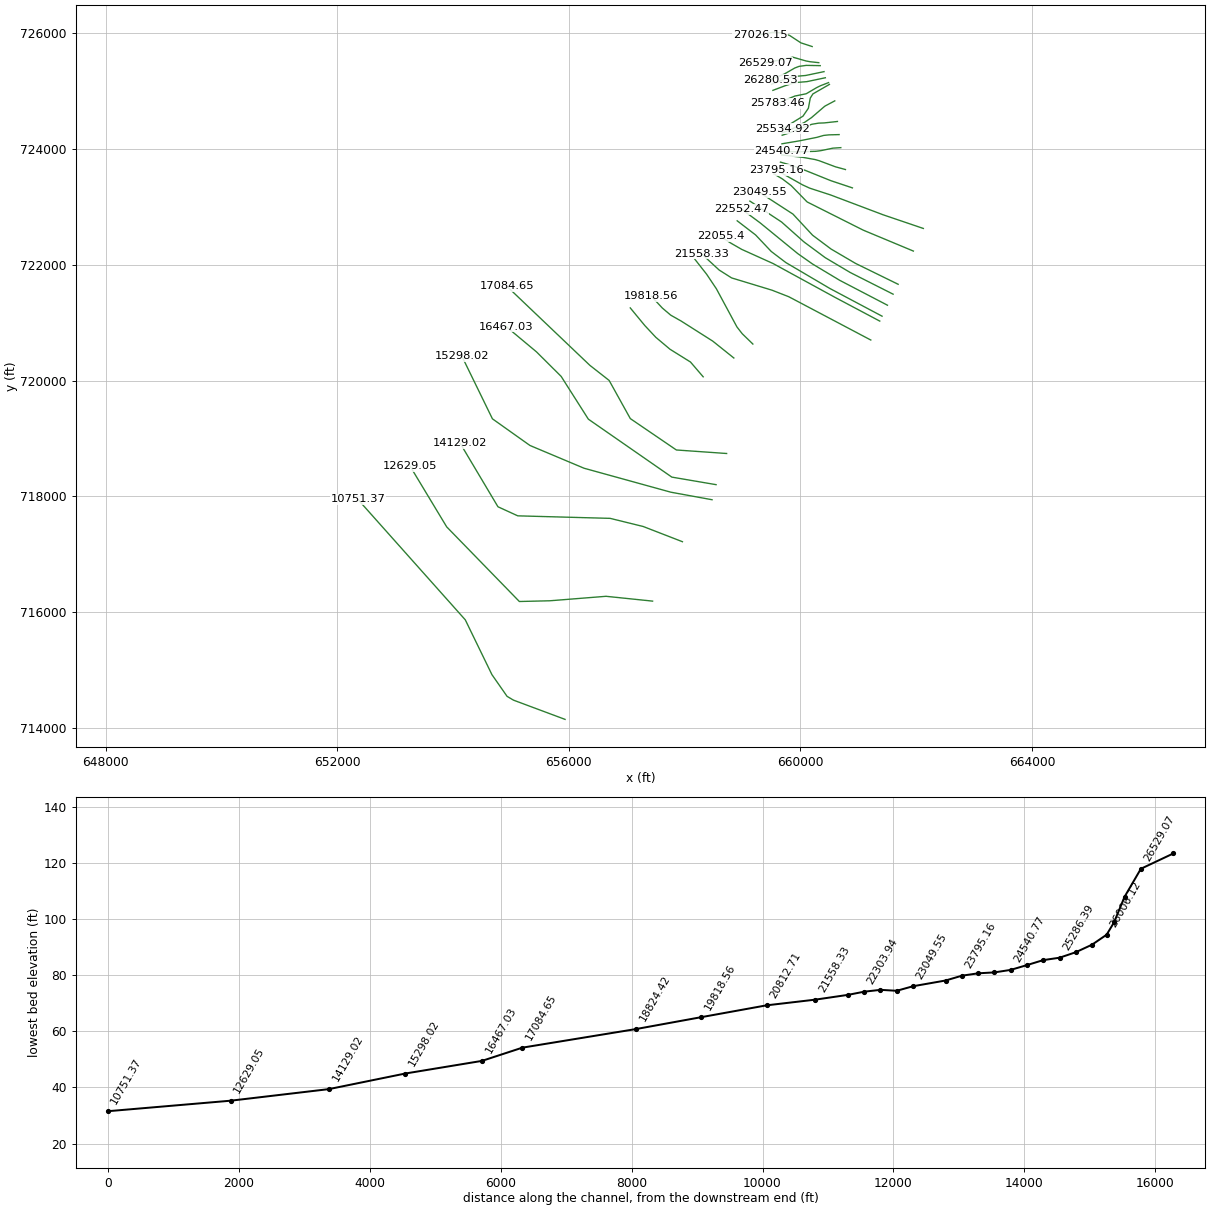
HEC-RAS study 4379_ras.prj: 4379

--- 4379_ras.g01 (geometry) --- (continued)

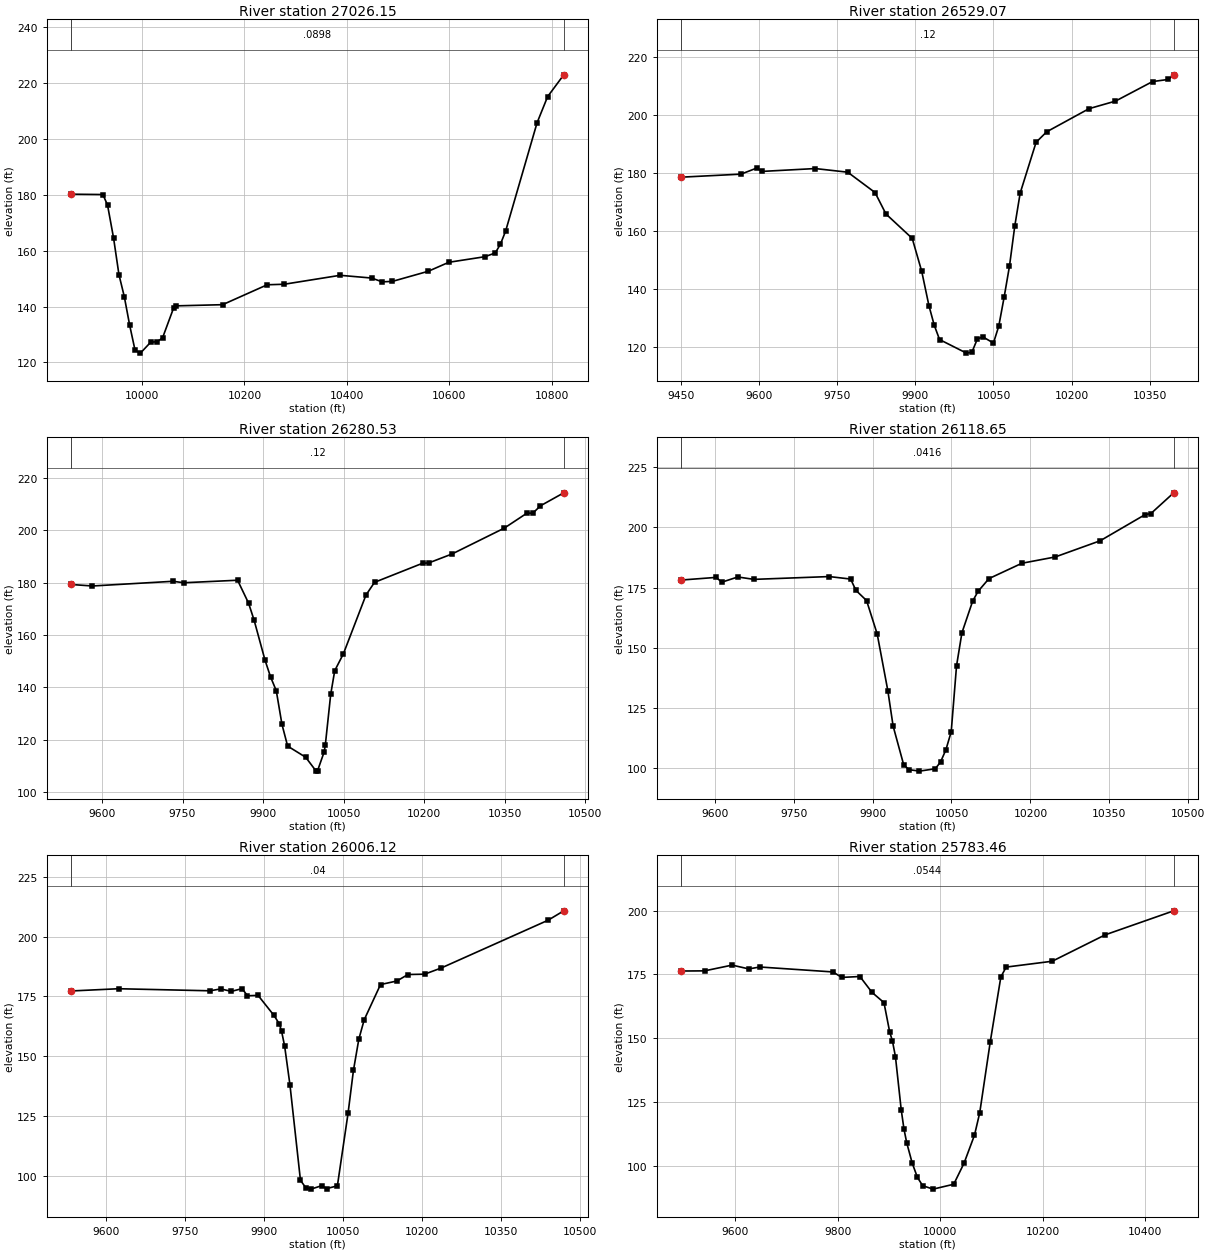
Type RM Length L Ch R = 1 ,27026.15,497.074600,497.074600,497.074600
XS GIS Cut Line= 6
660204.958149273725771.375502459660010.914864381725834.594985555
659814.943438523725963.057172207659691.374721867726006.387150266
659522.424183326726016.714753823659304.552799213725975.914928824
#Sta/Elev= 30
9861.718180.13139923.524180.01029932.571176.21549944.339164.45159954.823151.4062
9965.307143.49789975.792133.30089986.276124.36929996.761 123.339   10017127.2692
10029.07127.385810039.97128.762910061.78139.556310067.01140.2349 10157.3140.6478
10244.49147.765810277.76147.954310386.95151.1488 10448.7150.1678   10469148.8112
10489.12 148.97510559.25152.595110599.28155.799410669.76157.7908   10690159.1277
10700.12 162.25110710.33166.965510771.74205.649510792.34214.9937 10823.9222.7893
#Mann= 3 , 0 , 0
9861.718  0.0898       09861.718  0.0898       0 10823.9  0.0898       0
#XS Ineff= 2 , 0
       0                               0
Bank Sta=9861.718,10823.9
Exp/Cntr=0.3,0.1

Type RM Length L Ch R = 1 ,26529.07,248.537300,248.537300,248.537300
XS GIS Cut Line= 6
660319.217995203725492.929914785660173.315783627725508.258130939
660099.561227391725522.029574803659868.916282457725588.053643529
659675.855332522725543.710964798659395.068990172725492.047170162
#Sta/Elev= 30
9450.253178.52769565.043179.57289595.305181.66969605.463180.51469707.626   181.5
9770.066180.24659822.513173.23369843.491165.83889893.951 157.421 9912.17146.0653
9926.095134.18629936.267127.4604 9946.46122.54479998.133117.8692 10008.6118.2039
10018.99122.725610029.38 123.49710049.92 121.34610060.18127.196110070.45137.1556
10080.72147.843710090.98161.775210101.25173.025410131.85190.556910152.18194.1634
10233.52202.144310284.36204.754810355.54 211.48710386.04212.226410396.14213.8121
#Mann= 3 , 0 , 0
9450.253    0.12       09450.253    0.12       010396.14    0.12       0
#XS Ineff= 2 , 0
       0                               0
Bank Sta=9450.253,10396.14
Exp/Cntr=0.3,0.1

Type RM Length L Ch R = 1 ,26280.53,161.881300,161.881300,161.881300
XS GIS Cut Line= 6
660344.446406577725441.399542621660102.976829694725445.835215532
659979.607942748725428.987720785659904.910607282725400.494903038
659720.745650543725294.723679328659480.782049204725200.276916733
#Sta/Elev= 30
9542.848179.29839582.302178.73079732.331180.52539752.335179.96829852.571180.9293
9872.992172.17169883.223165.72399903.686 150.336 9914.07143.89879924.631138.6732
9935.192125.81529945.754117.50229979.364113.23769998.843107.9233 10001.6108.1292
10013.79115.255410015.99117.971210025.99137.292310033.48146.337310049.65152.8123
10091.67175.259610107.59180.127510197.33187.443810208.33 187.53110251.97190.9689
10349.19200.850510391.76206.6252 10402.4206.560410416.67 209.40110460.04214.3571
#Mann= 3 , 0 , 0
9542.848    0.12       09542.848    0.12       010460.04    0.12       0
#XS Ineff= 2 , 0
       0                               0
Bank Sta=9542.848,10460.04
Exp/Cntr=0.3,0.1

Type RM Length L Ch R = 1 ,26118.65,112.531700,112.531700,112.531700
XS GIS Cut Line= 6
660410.161630689725337.922045031660090.463046947725270.955127446
659925.059634145725257.270242845659848.963501853725242.254475413
659717.976642362725201.258354452659504.288307203725120.622961332
#Sta/Elev= 30
9536.197178.10649602.851179.2075 9613.08177.19519643.767179.37859674.454178.3836
9817.492179.54819858.228178.51369868.364173.80859888.555169.58259908.746155.7068
9928.937132.23649939.033117.48179959.153101.38199969.155  99.3969989.15998.77992
10019.1999.7660910029.19102.583810039.33107.616810049.47115.1286 10059.6142.5078
 10069.8 156.19210090.29169.389410100.54173.415510121.23178.701710183.88185.0758
 10247.2187.689110332.71194.414610418.22205.2853 10428.9205.668310472.42214.3103
#Mann= 3 , 0 , 0
9536.197  0.0416       09536.197  0.0416       010472.42  0.0416       0
#XS Ineff= 2 , 0
       0                               0
Bank Sta=9536.197,10472.42
Exp/Cntr=0.3,0.1

Type RM Length L Ch R = 1 ,26006.12,222.661700,222.661700,222.661700
XS GIS Cut Line= 6
660432.861407565725231.989752945660113.162823823 725165.02283536
 659947.75941102 725151.33795076659871.663278729725136.322183328
659740.676419237725095.326062366659526.988084078725014.690669247
#Sta/Elev= 30
 9533.58177.26829623.454178.20169797.257177.33849817.625178.11939837.993177.1036
9858.361178.25289868.473175.26129888.664175.4202 9918.95167.02319929.046163.5133
9933.251160.51249939.142154.24819949.235138.07119969.23998.086499979.24195.03765
9989.24394.3977210009.2795.8150310019.2794.6269710039.4595.7838810059.72126.1063
10069.95144.0362 10080.2157.100110090.44 165.23310121.42179.945610152.57 181.439
10173.57184.145510205.21184.285910236.85 186.87410439.86206.8382 10469.8210.7811
#Mann= 3 , 0 , 0
 9533.58    0.04       0 9533.58    0.04       0 10469.8    0.04       0
#XS Ineff= 2 , 0
       0                               0
Bank Sta=9533.58,10469.8
Exp/Cntr=0.3,0.1

Type RM Length L Ch R = 1 ,25783.46,248.537300,248.537300,248.537300
XS GIS Cut Line= 6
660488.070307139725148.040086165660349.046932294725094.469172003
660282.274580532725061.533071563660101.702815127724955.567044475
659906.608210187724916.245412637659602.929861368724791.081745914
#Sta/Elev= 30
9494.224176.3465 9539.82176.41169593.579 178.6679626.017 177.1759647.779177.9221
9790.461175.98379807.472173.8427 9842.95174.19539866.602167.9728  9889.9163.9635
9901.111152.42379906.365149.00739912.322142.76669923.533122.03399928.948114.4047
9934.331 109.0119944.924101.12879955.20995.43997 9965.4992.201179985.73490.85036
10026.0592.7587510046.24101.042810066.59112.013510076.77120.743710097.34148.5804
10118.03174.0297 10128.4177.889610218.21180.1762 10321.8190.544710455.36199.9434
#Mann= 3 , 0 , 0
9494.224  0.0544       09494.224  0.0544       010455.36  0.0544       0
#XS Ineff= 2 , 0
       0                               0
Bank Sta=9494.224,10455.36
Exp/Cntr=0.3,0.1

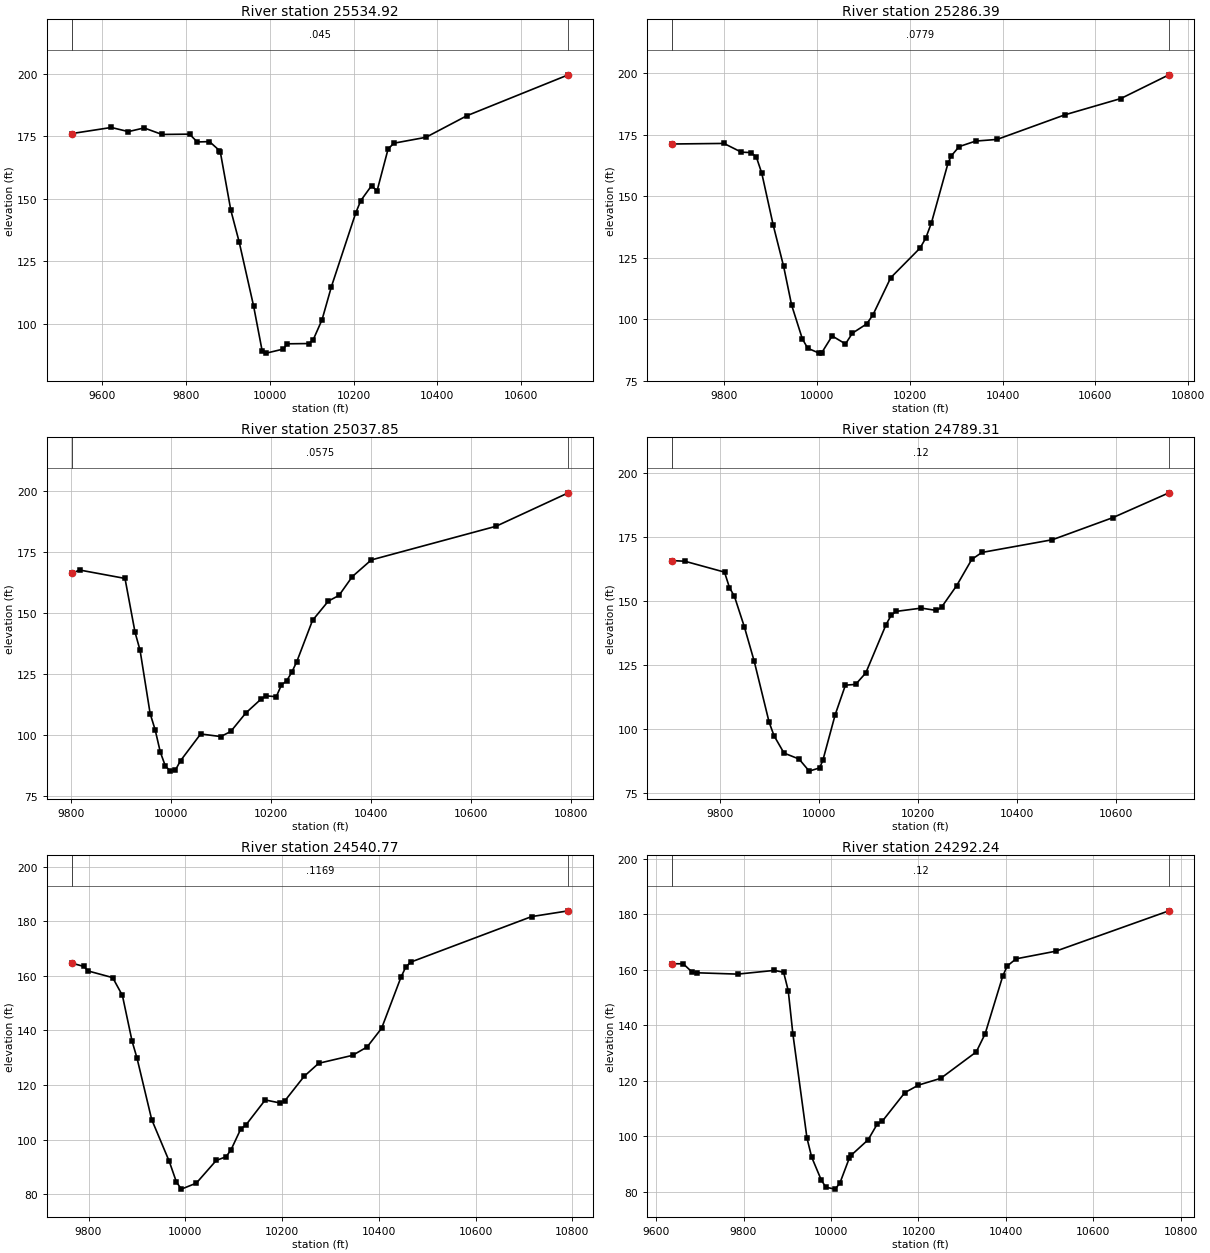
Type RM Length L Ch R = 1 ,25534.92,248.537300,248.537300,248.537300
XS GIS Cut Line= 6
660503.112188833725117.316242706660217.995241472724953.131619381
660172.405924419724881.037546203660139.504480877724705.648272772
660046.379410402724568.779555061659689.905941389724348.862220478
#Sta/Elev= 30
9527.379175.96699622.295178.41989663.035176.76919700.562178.2354 9743.26175.6309
9808.881175.74869827.293172.62739856.492172.76889880.172169.20789882.334168.6238
9907.384145.3328 9927.26 132.6479961.566107.1152 9981.9789.202119992.021 88.1593
10032.16 89.7666 10042.291.8857310093.4291.9922510103.9393.51607   10125101.5339
10147.35114.768610205.36144.258910217.38149.169710242.97155.120210256.15153.0388
10282.49169.791310296.21172.126810372.75 174.48910470.81183.144810712.29199.4812
#Mann= 3 , 0 , 0
9527.379   0.045       09527.379   0.045       010712.29   0.045       0
#XS Ineff= 2 , 0
       0                               0
Bank Sta=9527.379,10712.29
Exp/Cntr=0.3,0.1

Type RM Length L Ch R = 1 ,25286.39,248.537400,248.537400,248.537400
XS GIS Cut Line= 6
660595.342861351724832.877340195660423.836049401724741.508562368
660193.119901428724543.218176262660074.401652158724462.403671289
659858.199974793724348.323159165659688.061679758724281.239293914
#Sta/Elev= 30
9687.863171.19679799.499171.42889837.121167.87489857.684167.71439869.379165.8935
9881.073159.28459905.567138.3182  9928.1121.47139945.327105.74249968.51791.96207
9980.09888.1833910004.5986.1995410010.2386.3648110032.7293.1819810061.4489.92955
10076.2794.3096710106.91 98.044410120.27101.630110158.97116.865610221.95128.8603
 10234.3132.881710246.66 139.16610282.49163.4722 10289.3166.349810306.32170.1272
10341.76172.378910388.12 173.05810534.62183.079610654.73189.667910758.39199.3098
#Mann= 3 , 0 , 0
9687.863  0.0779       09687.863  0.0779       010758.39  0.0779       0
#XS Ineff= 2 , 0
       0                               0
Bank Sta=9687.863,10758.39
Exp/Cntr=0.3,0.1

Type RM Length L Ch R = 1 ,25037.85,248.537300,248.537300,248.537300
XS GIS Cut Line= 6
660641.445416773 724476.96561228660413.222805905724451.952915041
660316.569463403724448.352880416660197.780976385724428.351293918
 659794.91567279724274.114275269659686.918554005724239.324682911
#Sta/Elev= 30
9801.693166.20329818.207 167.4999908.528164.0783  9928.6142.05439938.635134.6908
9958.728108.85939968.844102.15869978.96193.193879989.07787.441519999.19685.34619
10009.3585.8551210019.4989.6214410059.67100.5332 10099.799.4675910119.71101.5381
10149.86109.107310180.05114.737510190.17116.117510210.65 115.74710220.89 120.528
10231.13122.185110241.37 125.64710251.67130.104110283.03146.935810314.65154.8201
10335.94157.143310362.58164.8378 10400.4171.628910649.57185.391410793.82199.0498
#Mann= 3 , 0 , 0
9801.693  0.0575       09801.693  0.0575       010793.82  0.0575       0
#XS Ineff= 2 , 0
       0                               0
Bank Sta=9801.693,10793.82
Exp/Cntr=0.3,0.1

Type RM Length L Ch R = 1 ,24789.31,248.537300,248.537300,248.537300
XS GIS Cut Line= 6
660670.811605153724250.258637953660498.307299558724245.786623176
660404.294333497724236.188521467660284.295938523724202.310598611
659987.987146857724142.949348657 659682.88727431724091.511093939
#Sta/Elev= 30
9704.145165.82369729.965165.56559809.992161.31689819.995155.25169829.998151.8591
9850.005139.96359870.012126.46349900.048102.70529910.06397.373919930.12290.63144
9960.49488.301159981.06583.5738810002.0484.8374410008.5687.7327510033.54105.6117
 10054.2117.161810074.79117.449410095.37121.936910136.17140.745110146.37144.3908
10156.57145.971310207.56147.262610238.16146.350710248.36147.604310278.95 156.035
10309.55166.306910329.95169.0026 10472.5 173.98110594.44 182.60110707.75 192.297
#Mann= 3 , 0 , 0
9704.145    0.12       09704.145    0.12       010707.75    0.12       0
#XS Ineff= 2 , 0
       0                               0
Bank Sta=9704.145,10707.75
Exp/Cntr=0.3,0.1

Type RM Length L Ch R = 1 ,24540.77,248.537300,248.537300,248.537300
XS GIS Cut Line= 6
660699.992849501724024.979431546660565.063438275724016.397489308
660353.193360456723972.250615806 660264.65230439723961.461496786
659986.718936002723952.904404068659679.278176296723959.177499942
#Sta/Elev= 30
9764.807164.66859789.815163.44499799.821 161.7359849.917159.32719870.001152.7925
9890.085135.98369900.127129.89859930.531107.34069966.82692.028959981.52684.51251
9991.80881.8677610022.7384.0580710063.8792.3671810084.2393.7290410094.4196.24829
10114.77103.958310124.87105.273910165.16114.531410195.38113.438110205.46114.1499
10245.54123.1697 10275.6 127.95310345.65130.865510375.65133.923110405.66140.7686
10445.66159.456210455.66163.213410465.66164.9933 10715.7181.684410791.46183.7932
#Mann= 3 , 0 , 0
9764.807  0.1169       09764.807  0.1169       010791.46  0.1169       0
#XS Ineff= 2 , 0
       0                               0
Bank Sta=9764.807,10791.46
Exp/Cntr=0.3,0.1

Type RM Length L Ch R = 1 ,24292.24,248.537400,248.537400,248.537400
XS GIS Cut Line= 6
660779.687708592723646.928372733660608.014072375723693.662092248
660325.205761752723799.305928851660257.373128074723818.794567077
660047.914946873723856.683960801659677.644256247723899.267098077
#Sta/Elev= 30
9636.671162.22829662.143 162.2079682.778159.13749693.096158.96939786.536158.4831
9870.564159.82799891.672159.14669902.226 152.511 9912.78 136.9979945.03799.40944
9955.80692.502469977.34484.407739988.11381.65378 10009.780.9732110020.5183.22806
10042.1392.2585410046.5893.2455110084.9598.7696110106.21104.548110116.83105.3539
10168.85115.750910199.85118.464110250.99120.915810332.21  130.4310352.46136.9335
10392.96157.834810403.07161.404210423.22163.993310513.91166.741210772.86181.3014
#Mann= 3 , 0 , 0
9636.671    0.12       09636.671    0.12       010772.86    0.12       0
#XS Ineff= 2 , 0
       09788.344                       0
Bank Sta=9636.671,10772.86
Exp/Cntr=0.3,0.1

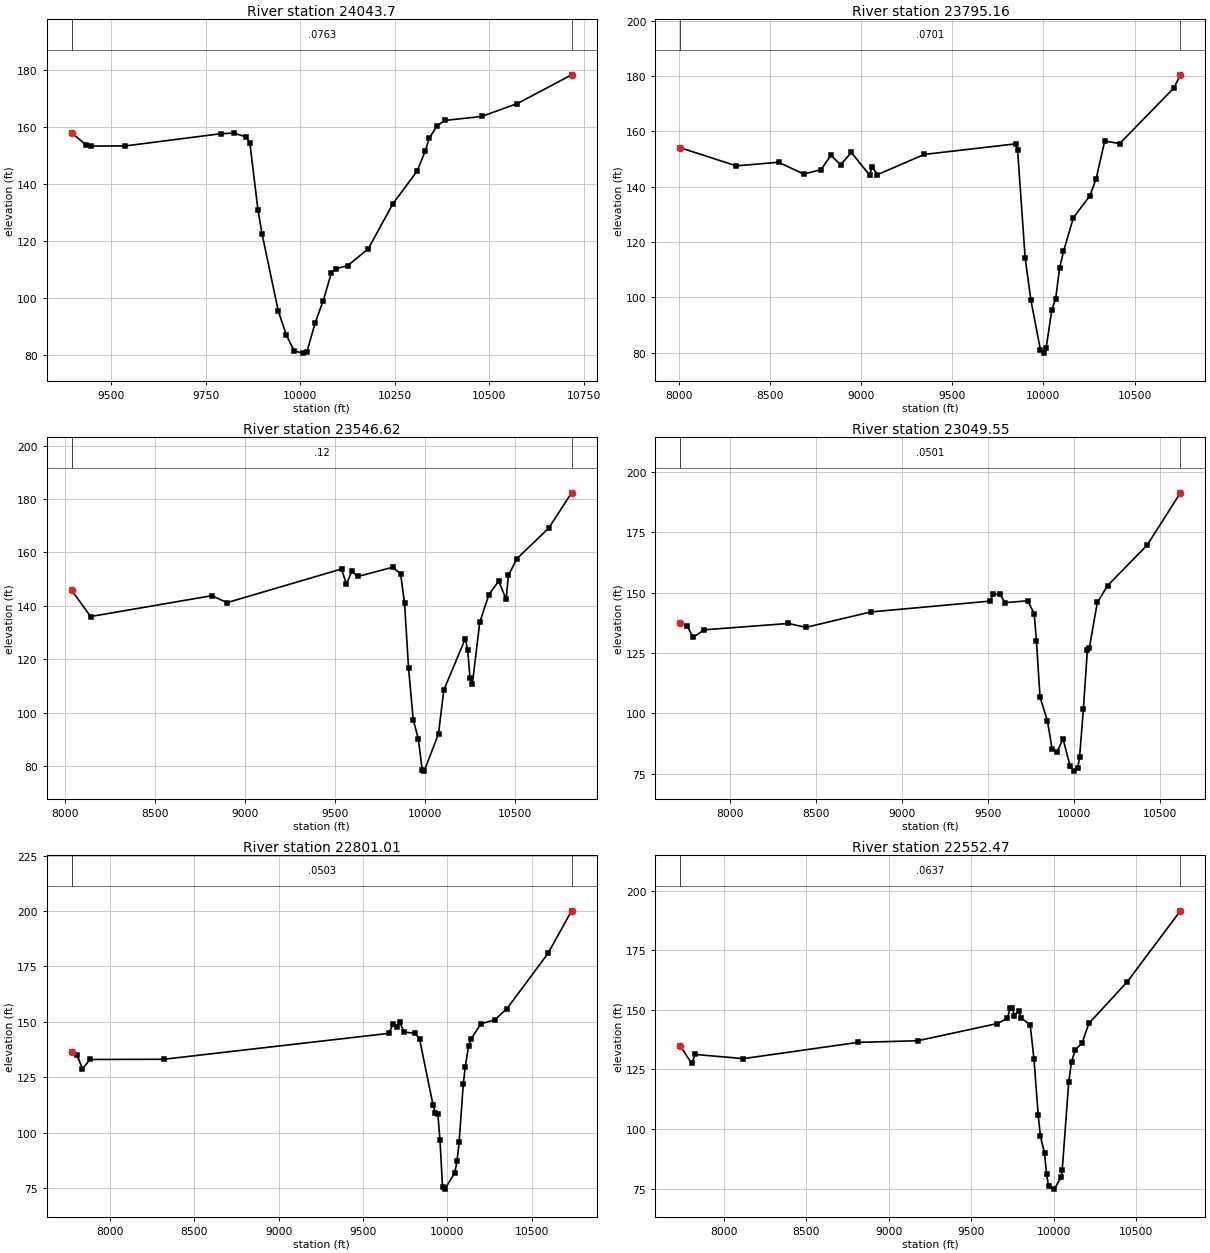
Type RM Length L Ch R = 1 , 24043.7,248.537300,248.537300,248.537300
XS GIS Cut Line= 6
660900.284573183723329.930900051660526.872123877723454.532226807
660101.261018635723626.121129293659922.088400185723692.929857496
659784.010904171  723738.2744803659657.485976013723774.776134068
#Sta/Elev= 30
9396.237158.08539433.251153.89999446.108153.39989538.209153.46759791.925157.7804
9824.051157.95649856.176156.70599866.885154.63869888.302131.1128 9899.01122.6787
9941.914 95.56629963.51986.988959984.04481.4195510006.7480.6490510017.5681.04295
 10039.2 91.138410060.8599.0792810082.49108.851910093.31110.247710125.77111.4091
10179.88117.320910244.81133.1238 10308.9 144.58510330.24  151.6110340.91156.1629
10362.26160.6375 10383.6162.429410479.11163.810410573.84168.352410717.09178.4446
#Mann= 3 , 0 , 0
9396.237  0.0763       09396.237  0.0763       010717.09  0.0763       0
#XS Ineff= 2 , 0
       09745.225                       0
Bank Sta=9396.237,10717.09
Exp/Cntr=0.3,0.1

Type RM Length L Ch R = 1 ,23795.16,248.537300,248.537300,248.537300
XS GIS Cut Line= 6
662125.322458547722629.110550346 661432.39034348722864.435003801
660520.852097837723208.666665151660165.568519876723324.134963297
660039.719393587723381.544324284659582.248865351723639.349334858
#Sta/Elev= 30
8008.017154.03648313.947147.53698546.444148.80388684.121144.57028779.641146.1493
8832.867151.31218887.321147.90378945.655 152.3779045.976144.15579060.338147.2132
9088.747144.32829345.793151.65029847.299155.47769858.018153.38749899.602114.2914
9930.98499.044319983.28781.0888710004.21 79.796710014.6781.6393210046.2295.44913
10067.3499.5258110088.48110.4661 10110.1116.551210164.46128.779810254.85 136.694
10289.52142.912410336.23156.491610418.27155.580110715.88175.674910751.83180.4384
#Mann= 3 , 0 , 0
8008.017  0.0701       08008.017  0.0701       010751.83  0.0701       0
#XS Ineff= 2 , 0
       0 9725.86                       0
Bank Sta=8008.017,10751.83
Exp/Cntr=0.3,0.1

Type RM Length L Ch R = 1 ,23546.62,497.074700,497.074700,497.074700
XS GIS Cut Line= 6
661953.197889509722238.415100011661085.405126211722600.692717525
660117.721076681723087.338538047659843.678424556723368.183400286
 659692.60675577723483.126099803659544.312543382723571.063955305
#Sta/Elev= 30
8036.216145.82748141.508135.99838815.774143.7991 8900.53  141.219536.852153.7981
9564.169148.03549593.598152.93729627.646 150.989 9820.52154.44029864.985152.0694
9887.218140.92249909.369116.84419935.26697.38511  9963.890.109719985.57378.47163
9996.45978.0883510076.0992.1141910105.44108.458310225.25 127.72510238.36123.2934
10251.46112.845910264.57 110.90310305.44133.860810356.26 144.211 10410.9149.2882
10451.89142.4202 10464.9151.417210511.92157.6632 10688.3169.0799 10816.1182.3266
#Mann= 3 , 0 , 0
8036.216    0.12       08036.216    0.12       0 10816.1    0.12       0
#XS Ineff= 2 , 0
       09705.098                       0
Bank Sta=8036.216,10816.1
Exp/Cntr=0.3,0.1

Type RM Length L Ch R = 1 ,23049.55,248.537300,248.537300,248.537300
XS GIS Cut Line= 6
661690.097220837721664.781456055660952.572786593722026.394099734
660532.046133391722273.155227341660212.161458385722512.423152152
659873.493632792722877.119641412 659289.78951271723255.283067043
#Sta/Elev= 30
 7712.27 137.2737750.812136.30987785.395131.43947850.046 134.589 8339.31137.2202
 8440.83135.60758818.222 141.995 9512.73146.49299527.886149.34829569.808149.2335
9597.755145.85739729.517146.59699767.808141.22119780.572129.87589801.215106.7748
 9844.3996.846749871.71985.111369901.22784.124219934.976 89.44899976.03278.13671
9998.12176.0490410020.17 77.178210031.2281.9930710053.36101.8346 10076.4126.3248
10087.93127.124810134.15145.951710194.38152.946610423.58169.666710616.97191.3437
#Mann= 3 , 0 , 0
 7712.27  0.0501       0 7712.27  0.0501       010616.97  0.0501       0
#XS Ineff= 2 , 0
       0 9540.86                       0
Bank Sta=7712.27,10616.97
Exp/Cntr=0.3,0.1

Type RM Length L Ch R = 1 ,22801.01,248.537300,248.537300,248.537300
XS GIS Cut Line= 6
661602.969433892  721493.9426581660861.729799717721868.731705901
660431.136271068722124.247621587660062.475371961722397.234783655
659677.516596791722739.812083877659129.222564433723101.697290437
#Sta/Elev= 30
7773.465136.34137804.391 135.1747837.562128.67297881.957132.9812 8317.97133.0694
9653.174144.76729678.794148.91059699.494147.76189718.168 149.7849744.417145.3631
9810.041144.7809 9836.29142.02349915.812112.3227 9929.48108.79259944.028108.5777
9956.81796.507529972.10575.222219985.519 74.429910044.5781.8340310057.4386.93258
10070.2995.5734410094.79121.810710106.68 129.71210126.48 139.01110142.08142.3723
10200.42149.128510280.69150.825410354.12155.982610596.97180.871910737.06200.1095
#Mann= 3 , 0 , 0
7773.465  0.0503       07773.465  0.0503       010737.06  0.0503       0
#XS Ineff= 2 , 0
       09694.493                       0
Bank Sta=7773.465,10737.06
Exp/Cntr=0.3,0.1

Type RM Length L Ch R = 1 ,22552.47,248.537400,248.537400,248.537400
XS GIS Cut Line= 6
661505.692379456721303.203335651660682.276373111721732.492195414
660209.405481352722016.352151415659955.072622654722195.490458261
659302.734680564722728.633620187 658984.59043592722963.353515344
#Sta/Elev= 30
7737.621134.75637805.387127.50447827.718131.26698119.081129.52318812.873136.3333
9175.711137.02279656.729144.21469718.988146.39519735.464150.62769748.611150.9665
9761.758147.59919788.052149.60019801.198146.69959857.626143.60989880.079129.5567
9906.372105.66519919.51996.985329944.29689.851669956.65281.103719969.00776.06343
10003.8474.7615910046.2580.0283610051.8382.8502510091.06119.670210108.16128.2196
10131.32133.308710171.58135.974810213.13144.278510446.03161.774810768.15191.5434
#Mann= 3 , 0 , 0
7737.621  0.0637       07737.621  0.0637       010768.15  0.0637       0
#XS Ineff= 2 , 0
       09768.869                       0
Bank Sta=7737.621,10768.15
Exp/Cntr=0.3,0.1

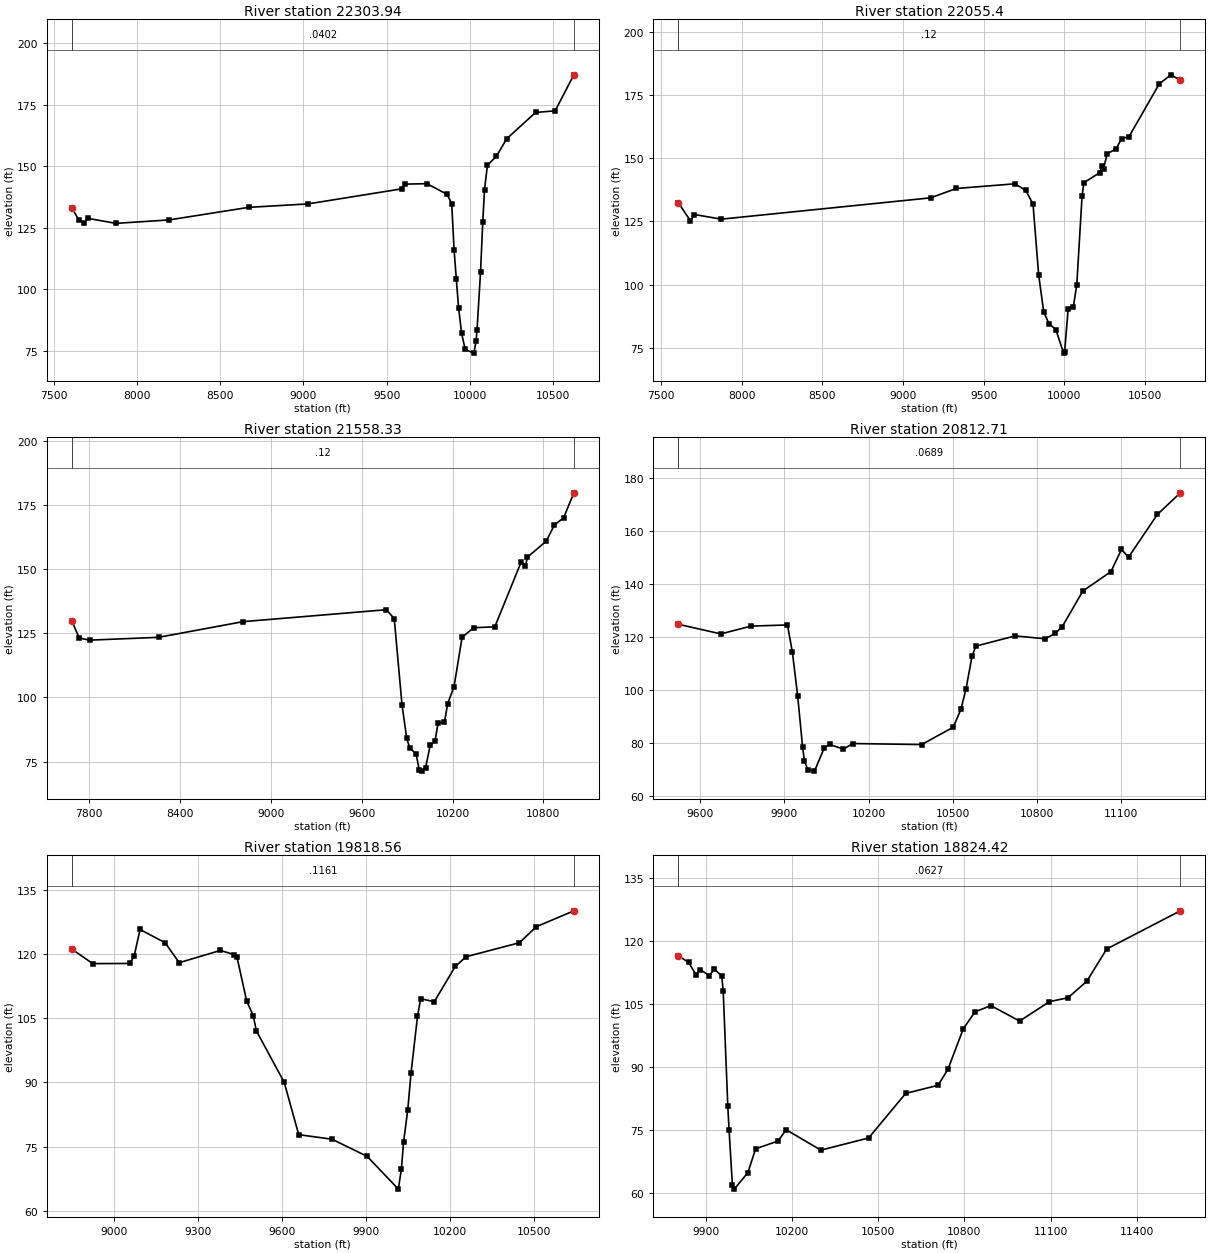
Type RM Length L Ch R = 1 ,22303.94,248.537300,248.537300,248.537300
XS GIS Cut Line= 6
661412.233513063721113.847097319660512.409905744721591.410205418
659750.401667188722039.886435268659497.957792533722231.868196383
659227.392363056722517.456896474658910.192375852722761.004448215
#Sta/Elev= 30
7609.115 133.2067650.814128.25677684.576126.9154 7707.09128.84057873.786126.8197
8192.601128.21258670.815133.31989027.297134.72239592.315140.8676 9610.07142.7627
9741.138142.94679862.535138.6105  9890.3134.81639904.545116.07779918.043 104.048
9931.54192.568929949.84982.118779971.18975.58488 10023.774.1064710036.9279.16663
10042.4183.6741810063.35107.030810076.84127.524510087.21140.496210104.87150.5332
10158.56 154.00410219.86161.149210394.31171.891310510.96172.518210623.58187.1605
#Mann= 3 , 0 , 0
7609.115  0.0402       07609.115  0.0402       010623.58  0.0402       0
#XS Ineff= 2 , 0
       09701.516                       0
Bank Sta=7609.115,10623.58
Exp/Cntr=0.3,0.1

Type RM Length L Ch R = 1 , 22055.4,497.074600,497.074600,497.074600
XS GIS Cut Line= 6
661372.241492078721029.102100478660607.298332402721434.765433598
 659529.66548564722023.297579107658987.854526581722267.936858778
 658791.34386671722381.009441468658627.222734688722490.611235568
#Sta/Elev= 30
7606.383132.48697681.982125.25057706.808127.74727873.834125.92249170.734134.3387
9330.439 138.0399694.077139.89159761.305137.25799805.878131.87539840.696104.0019
 9871.9689.327839904.39984.672219947.65282.284399995.23772.9731110001.71 73.3027
 10023.390.2194710055.6891.1786710077.27100.084810109.94135.021410120.88140.3029
10220.01144.309710231.16146.770410243.12145.9247 10265.7151.776110320.94 153.697
10355.11157.770810400.87158.509210589.19179.437510661.09 182.95410719.04180.8262
#Mann= 3 , 0 , 0
7606.383    0.12       07606.383    0.12       010719.04    0.12       0
#XS Ineff= 2 , 0
       09672.747                       0
Bank Sta=7606.383,10719.04
Exp/Cntr=0.3,0.1

Type RM Length L Ch R = 1 ,21558.33,745.612000,745.612000,745.612000
XS GIS Cut Line= 6
661217.794664927720701.821919163 659801.75745224721449.457192026
659511.864833691721562.618331131658813.344480918721774.980250619
658598.653332657721910.781171964658293.201892022722192.236400695
#Sta/Elev= 30
7686.911129.83847735.665123.1601 7804.02 122.3098259.723123.40588816.835129.5081
9763.738134.16529815.405130.69449867.07396.892579898.07483.990699918.74180.18927
9960.07577.999179980.74271.58051 10001.471.2766510022.0972.6213910053.1181.37644
10084.2582.8819110105.0790.1364910146.77 90.249210167.8397.47322   10210104.1679
10263.55123.479110340.29127.1422 10479.3127.505310654.18152.895210681.53151.1961
10694.59154.647910818.74160.857210871.98167.144710933.71169.991911000.96179.7051
#Mann= 3 , 0 , 0
7686.911    0.12       07686.911    0.12       011000.96    0.12       0
#XS Ineff= 2 , 0
       09689.774                       0
Bank Sta=7686.911,11000.96
Exp/Cntr=0.3,0.1

Type RM Length L Ch R = 1 ,20812.71,994.149300,994.149300,994.149300
XS GIS Cut Line= 6
659180.935623819720632.567741547658996.350109495720811.458768146
 658905.80891976720927.964140733658550.880699125721586.459223228
 658383.81693756721836.100263005658177.997404631722098.054629977
#Sta/Elev= 30
9522.386124.72249674.117121.07339781.762124.02169911.232124.45669928.735114.2015
9947.64797.523119965.15278.233569971.57973.12799 9983.3669.8494710007.4269.24574
10042.1478.0193810061.3679.3373610110.1377.5482610143.8179.6685410388.5579.27993
10501.4185.8167510528.5592.5641310547.04100.433410568.33112.704210581.74116.4567
10721.59120.325210828.97 119.22610865.23 121.325 10889.4123.851210962.79137.2827
11062.64144.591711100.18152.969911125.34150.049511227.98166.185311309.64174.3609
#Mann= 3 , 0 , 0
9522.386  0.0689       09522.386  0.0689       011309.64  0.0689       0
#XS Ineff= 2 , 0
       0                               0
Bank Sta=9522.386,11309.64
Exp/Cntr=0.3,0.1

Type RM Length L Ch R = 1 ,19818.56,994.149300,994.149300,994.149300
XS GIS Cut Line= 6
658851.917265566720391.856653994658488.232468338720682.721765122
657940.355067033721030.768081956657762.351057555721131.324744149
657617.869903892721253.712423796657426.167467842721458.922625754
#Sta/Elev= 30
8850.281121.19088925.062117.78949057.311117.82279073.023119.59339093.746 125.768
9182.911122.68819233.577118.00359380.239  120.879430.585119.87889439.102119.4256
9474.055109.06159497.221105.65189508.891102.03319607.96790.028349659.73477.78546
9778.262 76.72259903.752 72.711910015.1665.0457510026.0669.8470710033.8476.11216
 10048.783.6210210060.2592.1675110083.36105.436910094.91109.577110143.18108.8727
10218.09117.114910256.96119.407110446.82 122.66710507.37126.420210641.05130.1334
#Mann= 3 , 0 , 0
8850.281  0.1161       08850.281  0.1161       010641.05  0.1161       0
#XS Ineff= 2 , 0
       0                               0
Bank Sta=8850.281,10641.05
Exp/Cntr=0.3,0.1

Type RM Length L Ch R = 1 ,18824.42,1739.761300,1739.761300,1739.761300
XS GIS Cut Line= 6
658322.503121953720066.619064447658103.236809893720322.120703716
657749.759715901720542.455894382657505.335212808720748.171799105
657314.984598951720951.253831059657063.159008476721256.558105536
#Sta/Elev= 30
 9803.71116.39959839.815114.80159865.416111.87629880.168113.05619912.206111.6821
9929.418113.20639955.019111.58419960.263108.02179976.28280.55093 9980.6274.98646
9992.30161.80624    999960.8228410046.3464.7684610073.0370.41675 10151.172.26584
10179.4174.96154 10300.370.1060710466.4972.99882 10595.783.6189110708.3185.53896
 10742.989.3848910795.9798.9586110837.01103.042810892.35104.508410992.32 100.837
11096.12105.4585 11160.9106.388111226.29110.321411295.63118.001911551.78127.0809
#Mann= 3 , 0 , 0
 9803.71  0.0627       0 9803.71  0.0627       011551.78  0.0627       0
#XS Ineff= 2 , 0
       0                               0
Bank Sta=9803.71,11551.78
Exp/Cntr=0.3,0.1

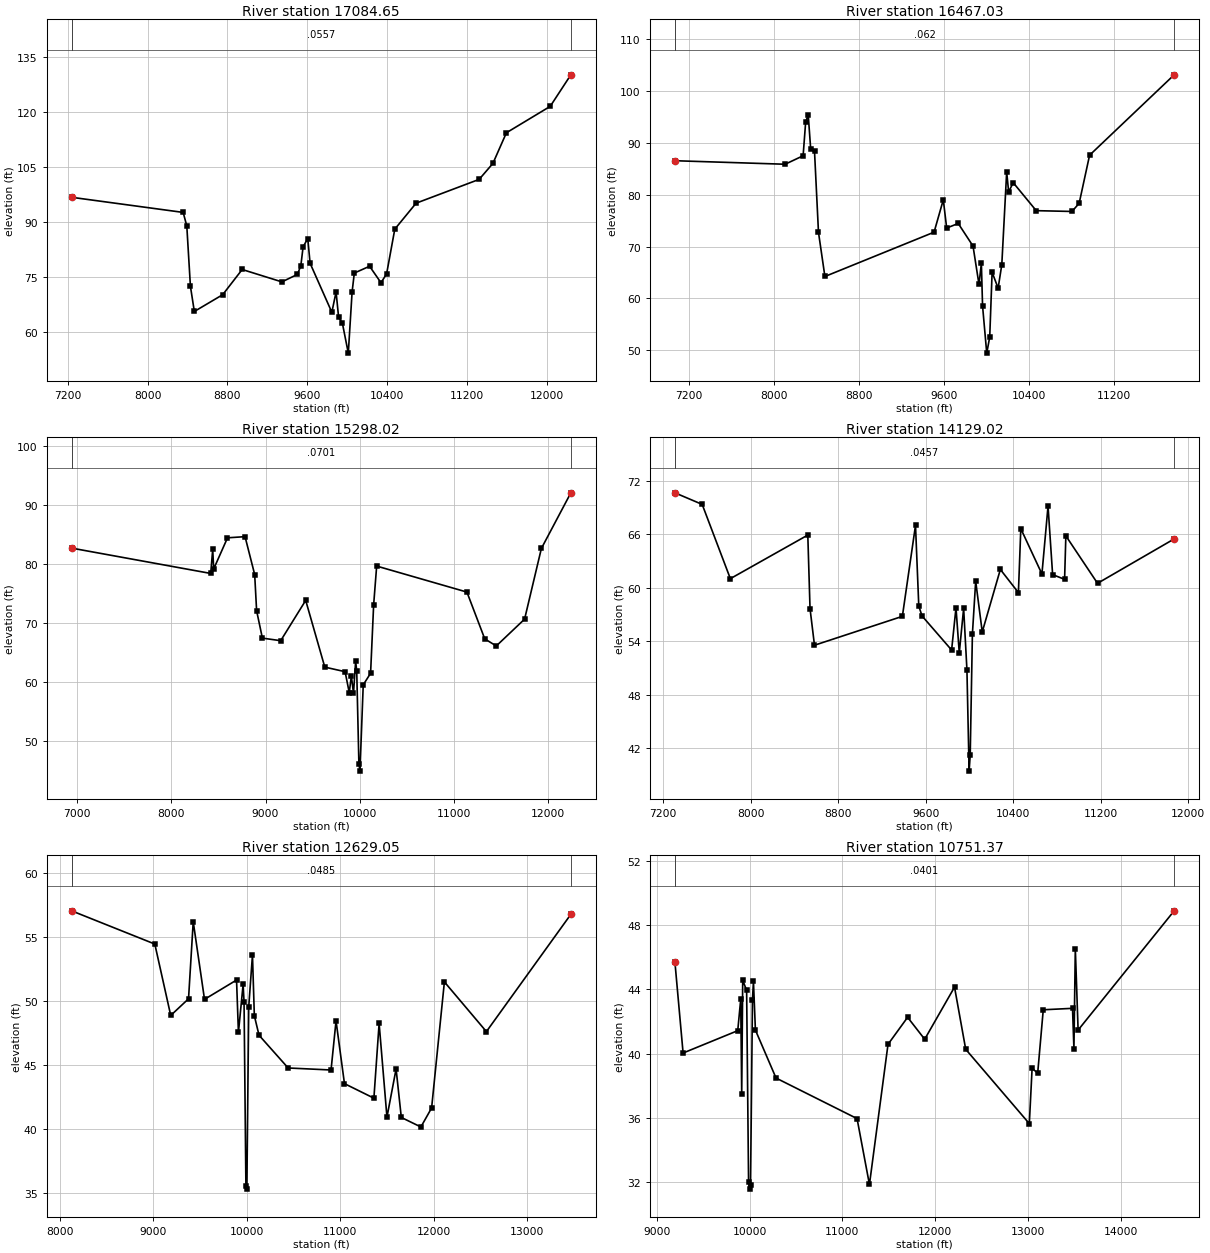
Type RM Length L Ch R = 1 ,17084.65,617.627200,617.627200,617.627200
XS GIS Cut Line= 6
 658727.42785275 718742.05301851657859.372297198718802.816907421
657063.968527287719344.817593485656698.305595241 720003.80350654
 656364.94744709 720265.16412066654928.893055527721633.321967672
#Sta/Elev= 30
7239.36596.690458356.85592.565348393.15788.86695 8429.4672.416218468.59265.54645
8752.72970.121298948.07276.996489345.94973.615839501.581 75.66199535.61678.03286
9558.43183.196259605.064 85.42569628.39978.690419846.29565.324899888.61770.87547
9914.11363.974299951.65562.37407 10011.154.1836310049.2370.8808910071.4776.02727
10224.3477.8808610338.6273.38315   1039575.8168610476.8887.99853 10690.395.08346
11321.98101.578511459.66105.9248   11595 114.292 12033.9121.493512240.57130.0953
#Mann= 3 , 0 , 0
7239.365  0.0557       07239.365  0.0557       012240.57  0.0557       0
#XS Ineff= 2 , 0
       09574.262        10200.01       0
Bank Sta=7239.365,12240.57
Exp/Cntr=0.3,0.1

Type RM Length L Ch R = 1 ,16467.03,1169.005000,1169.005000,1169.005000
XS GIS Cut Line= 6
658545.136186093718203.858574077657781.247297198718334.066907406
656339.158889925719335.019656826655869.040979581720074.257236319
655443.574550593720497.191762995654918.041260498720935.614065085
#Sta/Elev= 30
7069.23986.537738105.129 85.85978274.49387.494158298.22893.965218322.36695.40839
 8345.9488.709148381.66488.322958418.91572.740188479.25964.232279505.89272.77275
9592.60879.012599624.28273.570639733.07774.448329872.17270.09074 9928.1662.70084
9950.55666.783679961.75358.56461   1000149.4676210029.0552.5462810051.5465.05478
10108.0461.9708610142.6366.5074210188.4884.3764410207.1180.5281510249.8582.31211
 10466.576.9161410802.6176.7621210870.0978.3390510968.1287.6011611763.36103.0871
#Mann= 3 , 0 , 0
7069.239   0.062       07069.239   0.062       011763.36   0.062       0
#XS Ineff= 2 , 0
       09542.038        10275.61       0
Bank Sta=7069.239,11763.36
Exp/Cntr=0.3,0.1

Type RM Length L Ch R = 1 ,15298.02,1169.004900,1169.004900,1169.004900
XS GIS Cut Line= 6
658475.691741616717943.441907421657763.886186063718073.650240749
656265.228000283718487.418147728655330.365484446 718880.67679733
654682.288963854719341.011351869654152.775074959720426.080796286
#Sta/Elev= 30
6942.48982.679568418.68678.397988439.62382.462698450.09279.153368596.65484.42178
8782.92884.615818885.15878.213628905.60472.093678966.94267.463449161.17967.02904
9426.51673.842429629.10562.56221 9844.6361.788619888.79658.24632 9910.8861.07026
9933.75758.166969956.68863.539849968.15361.866639991.08446.2654210002.3444.97784
10037.14 59.567410115.1561.5229210147.6173.0906510179.6679.6441311137.5375.24738
 11326.767.3379811449.09 66.137411749.5370.6723611927.5682.6183712240.3392.02683
#Mann= 3 , 0 , 0
6942.489  0.0701       06942.489  0.0701       012240.33  0.0701       0
#XS Ineff= 2 , 0
       09437.553        10334.41       0
Bank Sta=6942.489,12240.33
Exp/Cntr=0.3,0.1

Type RM Length L Ch R = 1 ,14129.02,1499.962400,1499.962400,1499.962400
XS GIS Cut Line= 6
657964.143621325717218.455276772657286.447699398717481.187127352
656715.664191157717621.668691605655119.979914904717665.139068931
654777.775074959 717821.91412963654126.733408302 718915.66412963
#Sta/Elev= 30
7307.72470.674667556.67169.375647814.16361.033868522.15565.931538542.497 57.6714
8583.18253.557029386.66256.801969506.67567.021149536.68157.950069566.68856.84037
9836.74753.017189876.75657.767149906.75752.694019946.75757.699529976.75850.79309
9996.75839.4169310006.76  41.20710026.7654.8130310056.7660.7518610116.7655.04817
10282.26 62.067510447.2559.4667810469.2566.6506910662.2761.5591510718.1669.18319
10760.0361.4886310869.4560.9588910881.0865.84029 11170.6 60.511511871.0465.49654
#Mann= 3 , 0 , 0
7307.724  0.0457       07307.724  0.0457       011871.04  0.0457       0
#XS Ineff= 2 , 0
       09508.923        10448.41       0
Bank Sta=7307.724,11871.04
Exp/Cntr=0.3,0.1

Type RM Length L Ch R = 1 ,12629.05,1877.680300,1877.680300,1877.680300
XS GIS Cut Line= 6
657448.924736713716192.179480035656644.601047474716275.426012849
655675.025523243716198.209161437655147.583605734716185.521022549
653892.358408302717474.691907421 653258.67785272718525.039129645
#Sta/Elev= 30
8128.92957.073789018.26154.473169188.36148.885329378.73150.188949428.93856.22235
9549.58850.144759892.09851.656879912.20447.553899962.29251.311769972.30349.94734
9992.30535.5150610002.3135.2941910022.3149.5438710062.3253.6219110082.3448.86595
10132.4147.3373410443.7844.7752310902.4944.6176110955.76 48.462211045.8343.54937
11360.5242.4122511416.3548.2593411500.0940.9263411597.7944.6987611653.6240.90334
11862.9840.1584911977.5841.6456612114.2151.5117812563.3747.6208813466.0956.79893
#Mann= 3 , 0 , 0
8128.929  0.0485       08128.929  0.0485       013466.09  0.0485       0
#XS Ineff= 2 , 0
       09837.751        11329.43       0
Bank Sta=8128.929,13466.09
Exp/Cntr=0.3,0.1

Type RM Length L Ch R = 1 ,10751.37,4368.517800,4368.517800,4368.517800
XS GIS Cut Line= 6
655937.023812324714149.513035372655046.609059301714481.516496799
654935.475218499714547.114381897654673.608408295714922.608574076
654213.538963848715868.789129628652355.900074982717952.122462971
#Sta/Elev= 30
9195.29345.688379283.14140.033159872.19141.427859904.32143.377739915.03137.50785
9925.741 44.57849968.00443.934819989.018 31.96279999.52431.5443410010.0331.79672
10031.0443.3671310041.5544.4963410062.5841.4667110285.1138.4721211158.4835.94235
11291.9131.8333211492.0740.5745811703.3442.2609911887.4940.8919812209.0444.14408
12329.6340.2653313015.3135.6287513045.3639.0850413105.4638.7722213165.5642.73041
13481.11 42.820413496.1340.2966613511.1646.5491713541.2141.4639514576.6448.90172
#Mann= 3 , 0 , 0
9195.293  0.0401       09195.293  0.0401       014576.64  0.0401       0
#XS Ineff= 2 , 0
       09935.026        12041.03       0
Bank Sta=9195.293,14576.64
Exp/Cntr=0.3,0.1