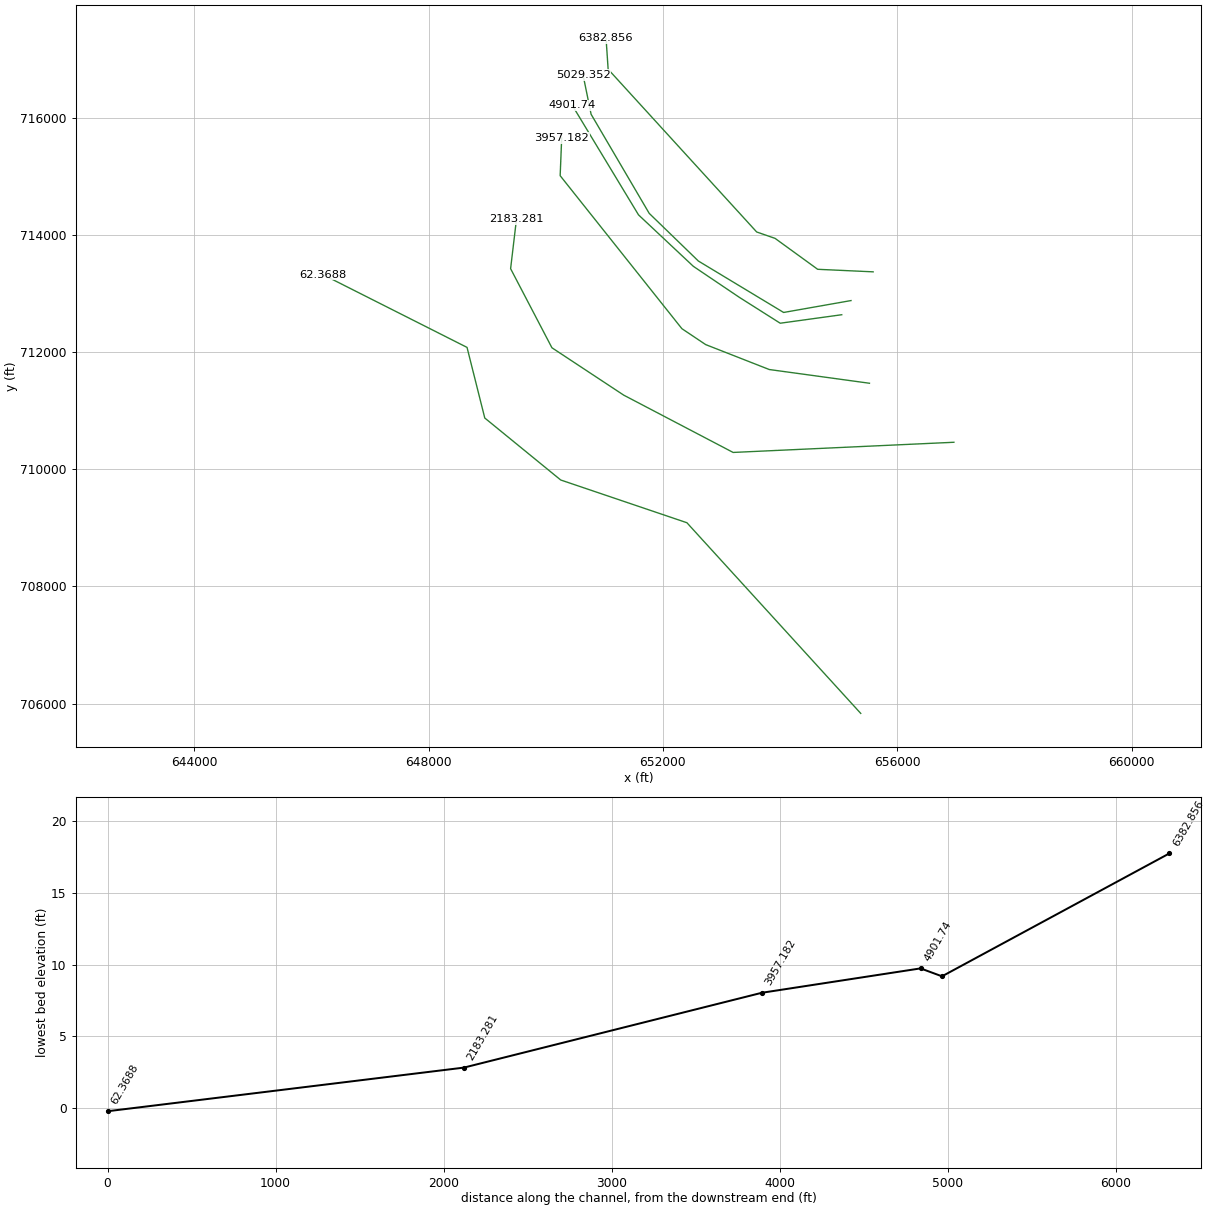
HEC-RAS study 4379_ras.prj: 4379

--- 4379_ras.g01 (geometry) --- (continued)

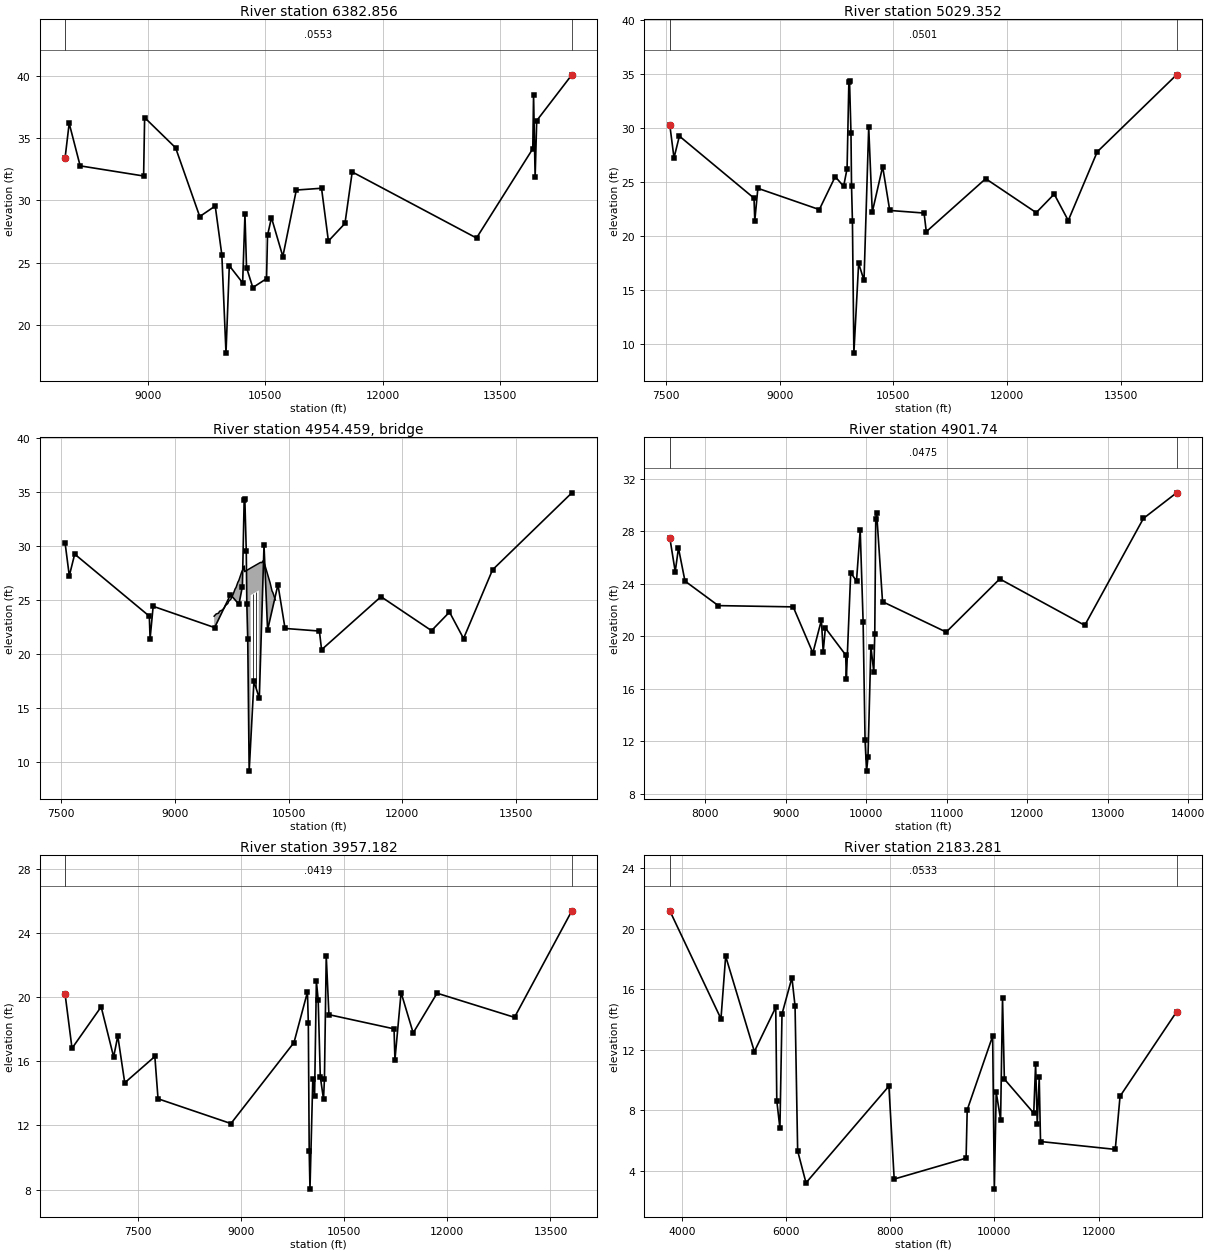
Type RM Length L Ch R = 1 ,6382.856,1353.504000,1353.504000,1353.504000
XS GIS Cut Line= 6
 655586.80285272 713368.78912963654640.622297168713412.191907406
653913.239669442713940.101851329653599.810875803714049.027532414
 651065.13471657716825.571159109651029.511186093717353.164129645
#Sta/Elev= 30
7941.08233.443497992.93936.186498133.08632.774218944.113 31.96138956.98536.64439
9352.71134.225449661.28428.710239859.26329.554139943.95625.63113 9996.8917.75733
10039.2424.7693610209.6723.3942710239.1928.9017110259.3924.6172210339.5123.01476
10515.0723.7283610527.6127.1948710577.7728.6196310723.4325.50338 10895.630.83461
11217.9430.9787211305.6626.74403 11517.328.1575611609.8932.2858313198.3926.98801
13917.5334.1442713927.5538.48595 13947.631.8468313967.6436.3975814416.8340.07398
#Mann= 3 , 0 , 0
7941.082  0.0553       07941.082  0.0553       014416.83  0.0553       0
#XS Ineff= 2 , 0
       09708.205        11031.21       0
Bank Sta=7941.082,14416.83
Exp/Cntr=0.3,0.1

Type RM Length L Ch R = 1 ,5029.352,127.612400,127.612400,127.612400
XS GIS Cut Line= 6
655209.230391473712878.589174464654059.220678985712675.646284029
652604.149452895713553.799684733651765.622297287 714367.05301851
650774.491062045716057.354349822650637.150075018 716728.16412963
#Sta/Elev= 30
7551.22630.254737606.29527.236627677.37629.250398662.36423.510778672.51921.42046
8713.13724.422739524.36422.45503 9733.86 25.50069845.17124.608119890.69226.24365
 9914.1534.252119922.93534.371899942.07129.554979949.33624.651059961.20821.44539
9980.3449.18004510043.1717.4858310114.1115.9127110176.14 30.074110223.3522.22483
10360.1826.4276110453.7222.3755810906.9122.1344410936.1220.4092511720.1325.31334
12387.0222.1724212624.3423.8877712809.8121.4434713192.3627.7972214239.1834.91744
#Mann= 3 , 0 , 0
7551.226  0.0501       07551.226  0.0501       014239.18  0.0501       0
#XS Ineff= 2 , 0
       09247.369        10196.68       0
Bank Sta=7551.226,14239.18
Exp/Cntr=0.3,0.1

Type RM Length L Ch R = 3 ,4954.459,,,
BEGIN DESCRIPTION:
END DESCRIPTION:
Bridge Culvert--1,0,-1,-1, 0
Deck Dist Width WeirC Skew NumUp NumDn MinLoCord MaxHiCord MaxSubmerge Is_Ogee
47.306200,33.000000,2.6,0, 32, 34, , , 0.95, 0, 0,0,,
 9517.88 9543.72 9576.92 9589.02 9625.32 9649.52 9668.05 9697.92 9710.02 9739.09
 9770.52 9794.72 9806.82 9831.02 9843.12 9881.18 9891.52 9903.62 9915.77 9920.64
10000.0010000.0010107.0010107.0010129.0410147.9810160.2010184.6510257.5610281.48
10293.4310325.53
   23.51   23.71   23.79   23.96   24.08   24.26   24.50   24.68   24.89   25.09
   25.57   26.03   26.16   26.65   26.80   27.59   27.75   27.82   28.15   27.63
   27.96   27.96   28.39   28.39   28.48   28.46   28.61   28.31   26.57   25.85
   25.69   25.01
 -976.49 -976.29 -976.21 -976.04 -975.92 -975.74 -975.50 -975.32 -975.11 -974.91
 -974.43 -973.97 -973.84 -973.35 -973.20 -972.41 -972.25 -972.18 -971.85 -972.37
 -972.04   25.46   25.89 -971.61 -971.52 -971.54 -971.39 -971.69 -973.43 -974.15
 -974.31 -974.99
 9517.88 9543.72 9576.92 9589.02 9625.32 9649.52 9668.05 9697.92 9710.02 9739.09
 9770.52 9794.72 9806.82 9831.02 9843.12 9881.18 9891.52 9903.62 9915.77 9920.64
 9967.28 9967.2810074.2810074.2810129.0410147.9810160.1010172.4210184.6510209.09
10257.5610281.4810293.4310325.53
   23.51   23.71   23.79   23.96   24.08   24.26   24.50   24.68   24.89   25.09
   25.57   26.03   26.16   26.65   26.80   27.59   27.75   27.82   28.15   27.63
   27.82   27.82   28.26   28.26   28.48   28.46   28.61   28.49   28.31   27.76
   26.57   25.85   25.69   25.01
 -976.49 -976.29 -976.21 -976.04 -975.92 -975.74 -975.50 -975.32 -975.11 -974.91
 -974.43 -973.97 -973.84 -973.35 -973.20 -972.41 -972.25 -972.18 -971.85 -972.37
 -972.18   25.32   25.76 -971.74 -971.52 -971.54 -971.39 -971.51 -971.69 -972.24
 -973.43 -974.15 -974.31 -974.99
Pier Skew, UpSta & Num, DnSta & Num=  ,10035.17, 2 ,10002.44, 2 , 0 , 0 , 0 ,,
    3.00    3.00
 -971.90   28.10
    3.00    3.00
 -972.03   27.97
Pier Skew, UpSta & Num, DnSta & Num=  ,10071.83, 2 ,10039.11, 2 , 0 , 0 , 0 ,,
    3.00    3.00
 -971.75   28.25
    3.00    3.00
 -971.88   28.12
BR Coef=-1 , 0 , 0 ,, 0 ,,,0.8,0,1,0,
WSPro=,,,, 1 ,,,, 0 ,,,, 0 ,,,,-1 ,-1 ,-1 , 0 , 0 , 0 , 0 , 0
BC Design=,, 0 ,, 0 ,,,,,,

Type RM Length L Ch R = 1 , 4901.74,944.557200,944.557200,944.557200
XS GIS Cut Line= 6
 655051.38592115712636.990495369654001.236996025712492.031287909
653305.859391958712932.471379563652519.422865838713462.555667892
651583.330630511714341.011351869650454.858408302716207.330796316
#Sta/Elev= 30
7559.01327.492387626.02824.925627666.40726.720427747.16624.207428161.05322.33784
9091.886 22.24159336.72918.733249442.24621.234859464.78518.804379491.39820.63665
9744.02118.57864 9752.63 16.78019806.60124.836339878.54824.212289924.59228.09302
9960.77421.110169984.89612.0941810003.76 9.7332210021.0810.7721810057.2619.22307
10093.4417.2799210105.5120.1973310117.5728.9321710128.97 29.382610201.9922.63784
 10993.420.32285 11658.424.3701612714.8220.8368813443.6328.9771513855.3630.92686
#Mann= 3 , 0 , 0
7559.013  0.0475       07559.013  0.0475       013855.36  0.0475       0
#XS Ineff= 2 , 0
       09167.403        10131.51       0
Bank Sta=7559.013,13855.36
Exp/Cntr=0.3,0.1

Type RM Length L Ch R = 1 ,3957.182,1773.901500,1773.901500,1773.901500
XS GIS Cut Line= 6
 655524.30285272711467.747462973653814.233408302711702.122462973
652729.163963854712127.469685197652323.690730453712398.970845729
650246.525074959715009.414129645650272.566741616715651.775240749
#Sta/Elev= 30
6438.43920.16093 6538.6716.803896962.59719.390157144.27916.26751 7204.8417.57148
7305.77514.654277743.81616.295667790.26213.660278851.08812.117119768.21717.16245
 9964.1620.307219976.92418.407879989.80310.39161   100018.03253710041.9214.86324
10068.0113.8621210094.1120.99227 10120.219.8366510151.31 15.036610198.0113.62481
10211.54  14.90210237.6322.5669910276.7818.9002211224.27 18.015611237.0716.08116
 11326.6 20.2788 11502.517.7616611850.0720.2371812977.04 18.732713811.27  25.368
#Mann= 3 , 0 , 0
6438.439  0.0419       06438.439  0.0419       013811.27  0.0419       0
#XS Ineff= 2 , 0
       08633.041        10098.14       0
Bank Sta=6438.439,13811.27
Exp/Cntr=0.3,0.1

Type RM Length L Ch R = 1 ,2183.281,2120.912200,2120.912200,2120.912200
XS GIS Cut Line= 6
656965.275074989710460.803018525653197.913963884710287.191907406
651330.624481797711265.206538662650105.909250617712073.349324808
649400.831555307713422.655595705649501.050839543714267.316188186
#Sta/Elev= 30
3772.23221.178774753.54714.052014843.64218.180535394.22611.888385804.661 14.8061
5824.6828.6426985884.7466.8244795924.78914.36618 6114.9916.767526175.05414.89237
6225.1075.3331036385.2773.2239437975.8479.6082618077.4453.4729879457.0794.853306
9478.6328.041092 9967.0112.91111    99992.80917510034.919.20581610119.317.398681
10156.33 15.441510191.5110.0722810755.447.82220910790.8711.0653110822.767.096836
10860.3610.2023210885.355.95094812319.695.43207312411.558.93971913495.5814.51097
#Mann= 3 , 0 , 0
3772.232  0.0533       03772.232  0.0533       013495.58  0.0533       0
#XS Ineff= 2 , 0
       07878.349         10434.4       0
Bank Sta=3772.232,13495.58
Exp/Cntr=0.3,0.1

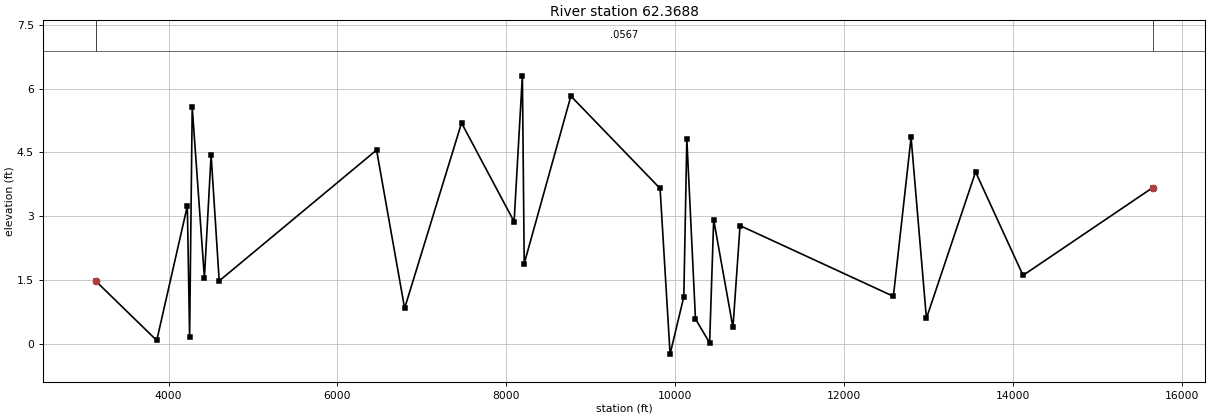
Type RM Length L Ch R = 1 , 62.3688,0.000000,0.000000,0.000000
XS GIS Cut Line= 6
655374.989494234705834.776025549652409.034763873709087.852009326
650255.988919109709816.961241975648960.069044471710874.665574789
648657.319902152 712079.72588639646199.709217429713320.403744161
#Sta/Elev= 30
3140.3451.4748473859.9240.0870694222.2573.2434564249.2080.1771924280.0165.561874
4424.386 1.555394503.8014.4422194599.5641.4842256463.6844.5570616795.8760.841928
7470.073 5.192588092.6012.8745528190.6786.2992478212.4731.8922098765.123 5.82374
 9821.563.6553559940.224-0.2346210102.861.11468110138.58 4.8212410240.77 0.59244
10408.510.02849910456.572.92067910684.820.39119910768.912.78279312585.05 1.12274
 12794.64.853076 12976.40.60585913558.414.04243914120.871.61467615655.173.672687
#Mann= 3 , 0 , 0
3140.345  0.0567       03140.345  0.0567       015655.17  0.0567       0
#XS Ineff= 2 , 0
       07748.826        10994.25       0
Bank Sta=3140.345,15655.17
Exp/Cntr=0.3,0.1